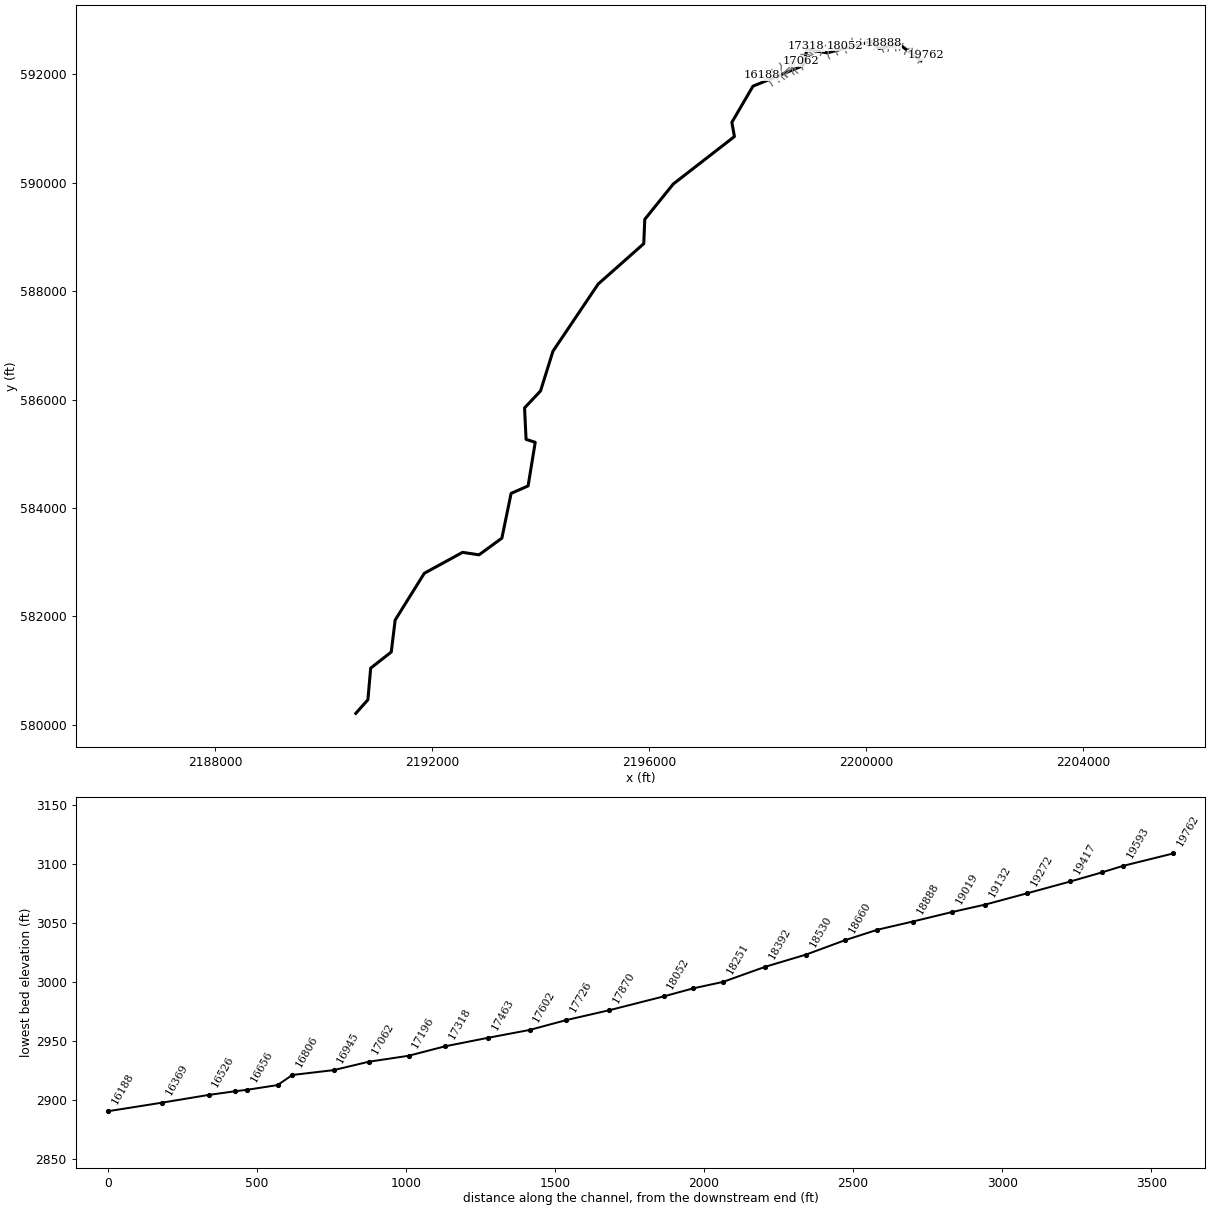
--- SUGARCK.prj (project) ---

Proj Title=SUGARCK
Current Plan=p01
Default Exp/Contr=0,0
English Units
Geom File=g01
Flow File=f01
Plan File=p01
BEGIN DESCRIPTION:
----------MODEL BY WOOD PLC 2022----------
AFH study
Randolph County, WV
HEC-RAS Version: RAS 6.2
Vertical Datum: NAVD88
Projection: NAD 1983 StatePlane West Virginia S FIPS 4702 (US Feet)
Terrain: 1-meter LIDAR (FEMA Region III 3DEP collected 2016-2018)
Land Use: 2019 NLCD
Hydrologic Method:
WV SIR2010-5033 regression equations
Additional Model Notes:
None
END DESCRIPTION:
DSS Export Rating Curves= 0
DSS Export Rating Curve Sorted= 0
DSS Export Volume Flow Curves= 0
DXF OffsetX= 0
DXF OffsetY= 0
DXF ScaleX= 0
DXF ScaleY= 0

--- SUGARCK.p01 (plan) ---

Plan Title=Floodplain
Program Version=6.20
Short Identifier=Floodplain
Geom File=g01
Flow File=f01
Subcritical Flow
K Sum by GR= 0
Std Step Tol= 0.01
Critical Tol= 0.01
Num of Std Step Trials= 20
Max Error Tol= 0.3
Flow Tol Ratio= 0.001
Split Flow NTrial= 30
Split Flow Tol= 0.02
Split Flow Ratio= 0.02
Log Output Level= 0
Friction Slope Method= 1
Unsteady Friction Slope Method= 2
Unsteady Bridges Friction Slope Method= 1
Parabolic Critical Depth
Global Vel Dist= 0 , 0 , 0
Global Log Level= 0
CheckData=True
Encroach Param=-1 ,0,0, 0
Mapping Interval=1HOUR
Computation Time Step Use Courant=        0
Computation Time Step Use Time Series=    0
Computation Time Step Count To Double=0
Computation Time Step Max Doubling=0
Computation Time Step Max Halving=0
Computation Time Step Residence Courant=0
Run HTab= 0
Run UNet= 0
Run Sediment= 0
Run PostProcess= 0
Run WQNet= 0
Run RASMapper=-1
UNET Theta= 0
UNET Theta Warmup= 0
UNET ZTol= 0
UNET ZSATol= 0
UNET MxIter= 0
UNET Max Iter WO Improvement= 0
UNET MaxInSteps= 0
UNET DtIC= 0
UNET DtMin= 0
UNET MaxCRTS= 0
UNET WFStab= 0
UNET SFStab= 0
UNET WFX= 1
UNET SFX= 1
UNET Gravity=32.174
UNET 1D Methodology=Finite Difference
UNET DSS MLevel= 1
UNET Pardiso=0
UNET DZMax Abort= 0
UNET Use Existing IB Tables= 0
UNET Froude Reduction=False
UNET Froude Limit= 0
UNET Froude Power= 0
UNET D1 Cores= 0
UNET WindReference=Eulerian
UNET WindDragFormulation=Hsu (1988)
UNET D2 Coriolis=0
UNET D2 Cores= 0
UNET D2 Theta= 1
UNET D2 Theta Warmup= 1
UNET D2 Z Tol= 0.01
UNET D2 Volume Tol= 0.01
UNET D2 Max Iterations= 20
UNET D2 Equation= 0
UNET D2 RampUpFraction=0.1
UNET D2 TimeSlices= 1
UNET D2 Turbulence Formulation=Non-Conservative (original)
UNET D2 Eddy Viscosity=0.3
UNET D2 Transverse Eddy Viscosity=0.1
UNET D2 Smagorinsky Mixing=0
UNET D2 BCVolumeCheck=0
UNET D2 Cores=0
UNET D2 SolverType=PARDISO (Direct)
UNET D2 Minimum Iterations= 2147483647
UNET D2 Maximum Iterations= 2147483647
UNET D2 Restart Number= 10
UNET D2 Relaxation Coeff=1.3
UNET D2 SOR Precondition Iterations= 10
UNET D2 ILUT Maximum Fill= 8
UNET D2 ILUT Tolerance=1E-08
UNET D1D2 MaxIter= 0
UNET D1D2 ZTol=0.01
UNET D1D2 QTol=0.1
UNET D1D2 MinQTol=1
Write IC File= 0
Write IC File at Fixed DateTime=0
Write IC File at Sim End=0
Echo Input=False
Echo Parameters=False
Echo Output=False
Write Detailed= 0
HDF Write Warmup=0
HDF Write Time Slices=0
HDF Flush=0
HDF Compression= 1
HDF Chunk Size= 1
HDF Spatial Parts= 1
HDF Use Max Rows=0
HDF Fixed Rows= 1
Calibration Method= 0
Calibration Iterations= 20
Calibration Max Change=0.05
Calibration Tolerance=0.2
Calibration Maximum=1.5
Calibration Minimum=0.5
Calibration Optimization Method= 1
WQ AD Non Conservative
WQ ULTIMATE=-1
WQ Max Comp Step=1HOUR
WQ Output Interval=15MIN
WQ Output Selected Increments= 0
WQ Output face flow=0
WQ Output face velocity=0
WQ Output face area=0
WQ Output face dispersion=0
WQ Output cell volume=0
WQ Output cell surface area=0
WQ Output cell continuity=0
WQ Output cumulative cell continuity=0
WQ Output face conc=0
WQ Output face dconc_dx=0
WQ Output face courant=0
WQ Output face peclet=0
WQ Output face adv mass=0
WQ Output face disp mass=0
WQ Output cell mass=0
WQ Output cell source sink temp=0
WQ Output nsm pathways=0
WQ Output nsm derived pathways=0
WQ Create Restart=0
WQ Fixed Restart=0
WQ System Summary=0
WQ Write To DSS=0
Sorting and Armoring Iterations= 10
XS Update Threshold= 0.02
Bed Roughness Predictor= 0
Hydraulics Update Threshold= 0.02
Energy Slope Method= 1
Volume Change Method= 1
Sediment Retention Method= 0
Sediment TS Multiplier= 1
Warm Up Method= 0
XS Weighting Method= 0
Number of US Weighted Cross Sections= 1
Number of DS Weighted Cross Sections= 1
Upstream XS Weight=0
Main XS Weight=1
Downstream XS Weight=0
Number of DS XS's Weighted with US Boundary= 1
Upstream Boundary Weight= 1
Weight of XSs Associated with US Boundary= 0
Number of US XS's Weighted with DS Boundary= 1
Downstream Boundary Weight= 0.5
Weight of XSs Associated with DS Boundary= 0.5
Percentile Method= 0
Sediment Output Level= 3
Mass or Volume Output= 0
Output Increment Type= 1
Profile and TS Output Increment= 1
Transport Output Increment 1
XS Output Flag= 0
XS Output Increment= 10
Read HDF5 Sediment Hotstart= 0
Sediment Hotstart Type= 0
Write Gradation File= 0
Read Gradation Hotstart= 0
Write HDF5 File= 1
Write Binary Output= 1
Write DSS Sediment File= 0
DSS Sediment Output Type= 1
SV Curve= 0
Specific Gage Flag= 0
Subcell Erosion Methods= 0
Subcell Deposition Methods= 0
Advection Scheme= 1
Matrix Solver= 0
Implicit Weighting Factor= 1
Maximum Outer Loop Convergence Iterations= 5
Convergence Maximum Absolute= 0.001
Convergence RMSE= 0.0001
Grain Fractions Max Abs Error= 0.001
Max Subgrid Regions= 1
Max Subgrid Length Scale= 3.402823E+38
Initial Layer Thickness= 3.402823E+38
Min Layer Thickness= 3.402823E+38
Max Layer Thickness= 3.402823E+38
Number of Layers= 5

--- SUGARCK.f01 (steady flow) ---

Flow Title=Flow
Program Version=6.20
Number of Profiles= 1
Profile Names=P100yr
River Rch & RM=SUGARCK,Main,19762
     416
River Rch & RM=SUGARCK,Main,17062
     468
River Rch & RM=SUGARCK,Main,14564
     560
River Rch & RM=SUGARCK,Main,11536
     812
River Rch & RM=SUGARCK,Main,9712
     910
River Rch & RM=SUGARCK,Main,6087
    1120
River Rch & RM=SUGARCK,Main,3005
    1260
Boundary for River Rch & Prof#=SUGARCK,Main            , 1
Up Type= 0
Dn Type= 3
Dn Slope=0.01381
DSS Import GetInterval= 0
DSS Import GetPeak= 0
DSS Import FillOption= 0

--- SUGARCK.g01 (geometry) ---

Geom Title=Geometry
Program Version=6.20

River Reach=SUGARCK         ,Main
Reach XY= 30
      2201011.22      592253.365     2200619.293      592551.108
     2200240.387      592478.192     2200095.421       592606.23
     2199281.714       592397.93     2198910.959      592459.962
     2198835.439      592161.786     2197913.997      591782.445
     2197525.108      591115.344     2197572.418      590853.626
2196444.81793474589978.0705056752195919.58562596589325.813047024
     2195900.968      588877.327     2195060.501      588132.746
     2194227.121      586894.117     2193997.871      586160.899
     2193703.458      585847.494      2193731.42      585267.372
2193900.14403002585213.571913841     2193768.766      584408.494
     2193455.641      584270.5592193285.10862924583444.826142301
      2192863.85583137.184655363     2192560.476      583183.103
2191855.49337076582796.924685381     2191318.114      581934.492
     2191245.876      581344.532     2190866.463      581046.189
     2190815.503      580464.078      2190592.16       580212.46

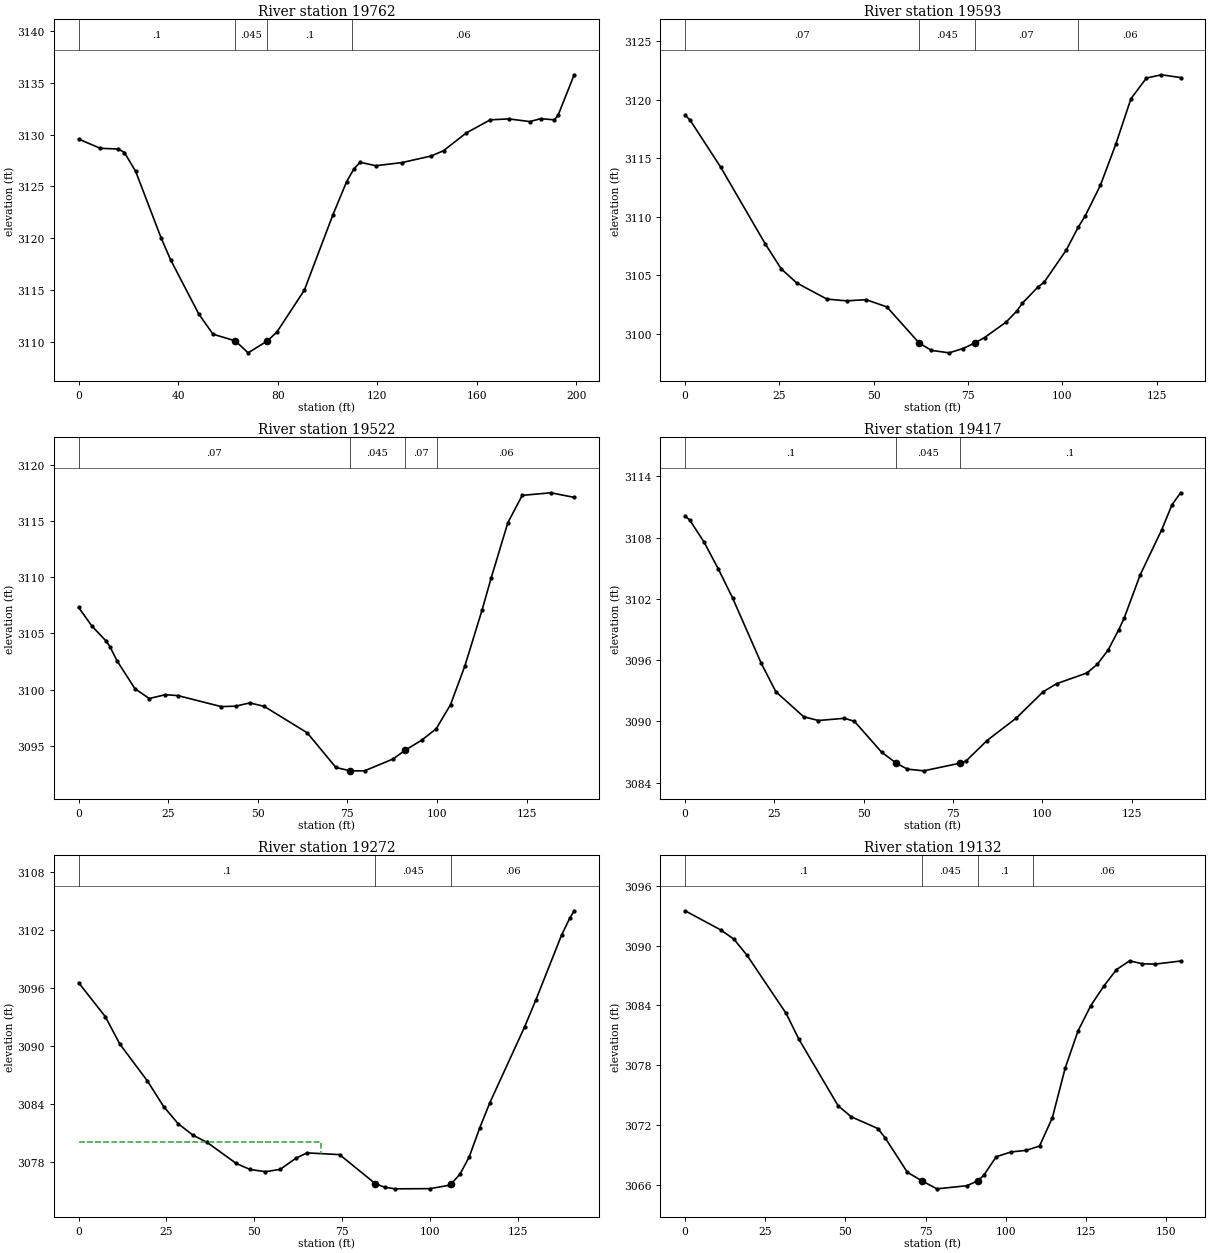
Type RM Length L Ch R = 1 ,19762   ,169.2,169.2,169.2
XS GIS Cut Line= 2
2200957.05386083592211.9514959792201095.61742638592354.857175133
#Sta/Elev= 30
       0 3129.57     8.7 3128.68      16 3128.61    18.4 3128.27    22.9 3126.46
    33.2 3119.99      37 3117.89    48.3 3112.67      54 3110.73      63 3110.08
    68.1 3108.93   75.833110.079    79.7 3110.95    90.7 3114.99   102.2 3122.28
   107.7 3125.47   110.6 3126.69   113.1 3127.33   119.4    3127   129.9  3127.3
   141.7 3127.94   146.6 3128.45   155.8 3130.17   165.4 3131.43   172.8 3131.52
   181.3 3131.26   185.6 3131.54   191.1 3131.43   192.6 3131.85   199.1 3135.78
#Mann= 4 ,-1,0
       0      .1       0      63    .045       0   75.83      .1       0
     110     .06       0
Bank Sta=63,75.83
XS Rating Curve= 0 ,0
Exp/Cntr=0.3,0.1

Type RM Length L Ch R = 1 ,19593   ,71.4,71.4,71.4
XS GIS Cut Line= 4
2200894.65229685592339.8489816772200889.75767567592378.679643015
2200937.07234705592423.3838497662200941.64066015592450.141112201
#Sta/Elev= 30
       0 3118.69     1.3 3118.28     9.4 3114.26    21.3 3107.65    25.5 3105.53
    29.6 3104.33    37.6 3102.95    42.8  3102.8      48  3102.9    53.5 3102.28
   62.073099.187    65.3 3098.56      70 3098.35    73.7 3098.72   76.743099.187
    79.4 3099.66    85.1 3100.98    87.9 3101.91    89.4 3102.59    93.5 3103.97
    95.2  3104.4     101 3107.12   104.2 3109.09   106.1 3110.09   110.1 3112.69
   114.2 3116.22   118.2  3120.1   122.3 3121.87   126.3 3122.15131.3757 3121.91
#Mann= 4 ,-1,0
       0     .07       0   62.07    .045       0   76.74     .07       0
  104.23     .06       0
Bank Sta=62.07,76.74
XS Rating Curve= 0 ,0
Exp/Cntr(USF)=0,0
Exp/Cntr=0.3,0.1

Type RM Length L Ch R = 1 ,19522   ,104.8,104.8,104.8
XS GIS Cut Line= 2
2200842.74335066 592341.459284012200848.43491883592479.609165816
#Sta/Elev= 30
       0 3107.31     3.7 3105.65     7.7 3104.31     8.8 3103.79    10.7 3102.57
    15.7 3100.09    19.7 3099.21    24.2 3099.55    27.7 3099.47    39.8 3098.49
    43.8 3098.53    47.8 3098.82    51.8 3098.51    63.8 3096.16    71.8 3093.08
    75.73092.787    75.8 3092.78    79.8 3092.78    87.8 3093.84    91.13094.607
    95.8 3095.52    99.8 3096.52   103.8 3098.67   107.8 3102.11   112.6 3107.08
   115.1 3109.89   119.8 3114.85   123.8 3117.27   131.8  3117.5   138.3 3117.09
#Mann= 4 ,-1,0
       0     .07       0    75.7    .045       0    91.1     .07       0
     100     .06       0
Bank Sta=75.7,91.1
XS Rating Curve= 0 ,0
Exp/Cntr(USF)=0,0
Exp/Cntr=0.3,0.1

Type RM Length L Ch R = 1 ,19417   ,144.6,144.6,144.6
XS GIS Cut Line= 4
2200711.87371727 592371.867291732200712.89869714 592396.95289541
2200778.16031283592456.9935818492200789.15683613592479.331630009
#Sta/Elev= 30
       0 3110.12     1.3 3109.73     5.3 3107.57     9.3 3104.94    13.3 3102.09
    21.3 3095.71    25.4 3092.91    33.2 3090.46    37.3 3090.09    44.6 3090.31
    47.4 3090.01      55 3086.99   59.143085.905    62.2 3085.33    66.8 3085.16
   76.853085.904    78.6 3086.11    84.5 3088.13    92.7 3090.33   100.2  3092.9
     104  3093.7   112.5 3094.75   115.4 3095.61   118.4 3096.99   121.4    3099
   122.9 3100.13   127.4 3104.38   133.4 3108.77   136.3 3111.24   138.7  3112.4
#Mann= 3 ,-1,0
       0      .1       0   59.14    .045       0   76.85      .1       0
Bank Sta=59.14,76.85
XS Rating Curve= 0 ,0
Exp/Cntr=0.3,0.1

Type RM Length L Ch R = 1 ,19272   ,140.6,140.6,140.6
XS GIS Cut Line= 3
2200615.33258168592445.8991071812200634.91106638592516.055344053
2200679.28896506 592567.93832853
#Sta/Elev= 30
       0 3096.55     7.6 3093.03    11.7  3090.2    19.6 3086.35    24.2 3083.71
    28.3 3081.94    32.5 3080.75    36.6 3079.98    44.9  3077.8    48.8 3077.18
    53.2 3076.95    57.4 3077.19    61.8 3078.33      65  3078.9    74.3 3078.72
    84.53075.703    87.1 3075.34    90.1 3075.17   100.1 3075.19   105.6 3075.55
  106.143075.702   108.6  3076.7   111.2 3078.47   114.2 3081.48   117.1 3084.11
     127 3091.98   130.2 3094.77   137.5 3101.48   139.8 3103.21   141.1 3104.01
#Mann= 3 ,-1,0
       0      .1       0    84.5    .045       0  106.14     .06       0
#XS Ineff= 2 , 0
         68.9691    3080
Permanent Ineff=
       F       F
Bank Sta=84.5,106.14
XS Rating Curve= 0 ,0
Exp/Cntr(USF)=0,0
Exp/Cntr=0.3,0.1

Type RM Length L Ch R = 1 ,19132   ,112.3,112.3,112.3
XS GIS Cut Line= 4
2200548.36456596592434.209409708 2200538.0858865592491.715687479
2200513.19815311592534.9812126042200511.24760429 592581.14163324
#Sta/Elev= 30
       0 3093.49    11.1 3091.57    15.2 3090.65    19.3 3089.03    31.5 3083.19
    35.5 3080.59    47.7 3073.93    51.8 3072.82    60.1 3071.64    62.3 3070.74
    69.3 3067.25    73.9 3066.38    78.5 3065.59    87.8  3065.9    91.23066.381
    93.1 3066.94      97 3068.81   101.6 3069.29   106.3 3069.45   110.5 3069.88
   114.5 3072.72   118.5  3077.7   122.5 3081.43   126.5 3083.98   130.5 3085.91
   134.5 3087.59   138.6 3088.47   142.6 3088.17   146.6 3088.14   154.5 3088.45
#Mann= 4 ,-1,0
       0      .1       0    73.9    .045       0    91.2      .1       0
  108.33     .06       0
Bank Sta=73.9,91.2
XS Rating Curve= 0 ,0
Exp/Cntr=0.3,0.1

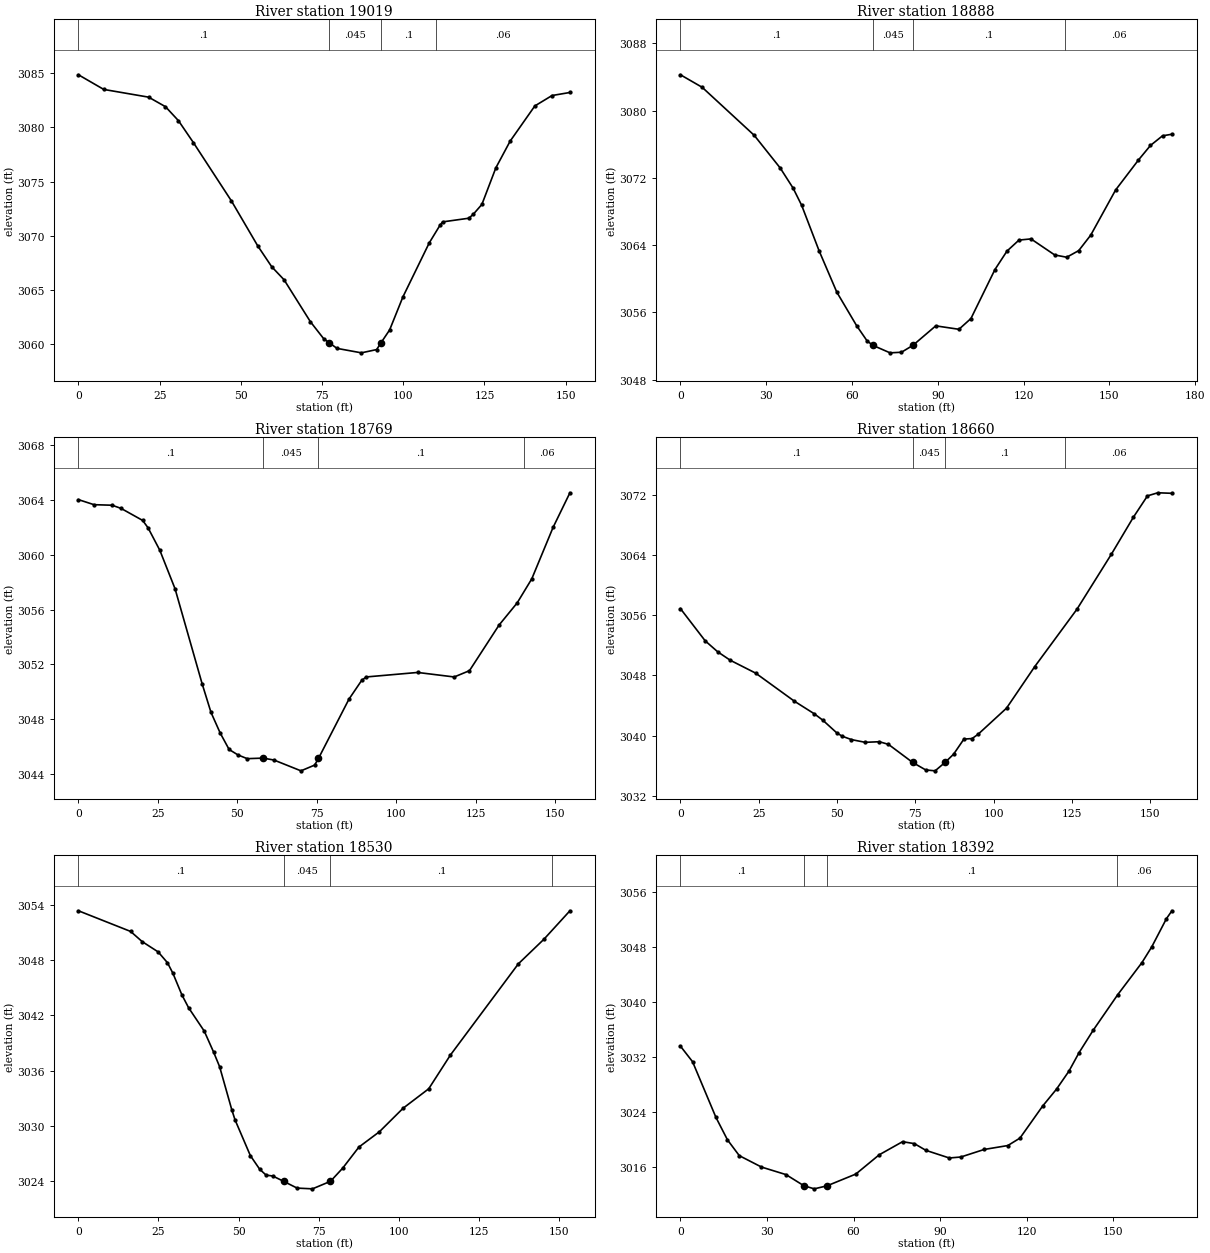
Type RM Length L Ch R = 1 ,19019   ,131.2,131.2,131.2
XS GIS Cut Line= 2
2200405.52743259592426.8328064742200431.91561226592575.848409322
#Sta/Elev= 30
       0 3084.83     7.8 3083.48    21.6 3082.77    26.8 3081.89    30.8  3080.6
    35.4 3078.58    47.1 3073.21    55.2 3069.07    59.5 3067.15    63.3 3065.95
    71.4 3062.09    75.5 3060.52    77.23060.151    79.6 3059.63    87.1 3059.22
    91.8 3059.52   93.15 3060.15    95.8 3061.33    99.9 3064.38     108 3069.35
   111.3 3070.97   112.1 3071.28   120.2 3071.62   121.6    3072   124.2 3072.89
   128.5 3076.26   132.9 3078.72   140.5 3081.96   145.8 3082.92   151.3  3083.2
#Mann= 4 ,-1,0
       0      .1       0    77.2    .045       0   93.15      .1       0
     110     .06       0
Bank Sta=77.2,93.15
XS Rating Curve= 0 ,0
Exp/Cntr(USF)=0,0
Exp/Cntr=0.3,0.1

Type RM Length L Ch R = 1 ,18888   ,119,119,119
XS GIS Cut Line= 4
2200322.84809265592410.4678643412200296.88177012592458.594960441
2200294.94670486 592498.420465532200317.67237046592572.398930295
#Sta/Elev= 30
       0 3084.25     7.6 3082.76    25.8 3077.05    34.9 3073.16    39.4 3070.77
    42.4 3068.72    48.5 3063.31    54.7 3058.39    61.6 3054.42    65.3 3052.59
    67.33052.071    73.3 3051.18    77.3 3051.25    81.3 3052.07    89.3 3054.39
    97.4 3053.98   101.6 3055.26     110 3061.09   114.2 3063.28   118.4 3064.59
   122.6 3064.73   130.9 3062.82   135.1 3062.55   139.3 3063.34   143.5 3065.18
   152.2 3070.55   160.2 3074.12   164.4 3075.85   168.6 3076.99   171.9 3077.18
#Mann= 4 ,-1,0
       0      .1       0    67.3    .045       0    81.3      .1       0
  134.56     .06       0
Bank Sta=67.3,81.3
XS Rating Curve= 0 ,0
Exp/Cntr=0.3,0.1

Type RM Length L Ch R = 1 ,18769   ,109,109,109
XS GIS Cut Line= 2
2200145.24919432592473.1588407112200259.59158505592577.280682549
#Sta/Elev= 30
       0 3064.04     4.9 3063.67    10.6 3063.63    13.4  3063.4    20.2 3062.52
    21.9 3061.98    25.6 3060.34    30.4 3057.52    38.9 3050.59    41.7 3048.49
    44.6 3046.98    47.4 3045.78    50.2 3045.38    53.1 3045.11    58.1 3045.15
    61.5 3045.01      70 3044.22    74.3 3044.64   75.51 3045.13    85.1 3049.46
    89.1 3050.83    90.5 3051.08   106.7 3051.41   118.2 3051.08     123 3051.54
   132.3 3054.87     138 3056.49   142.6 3058.25   149.3 3062.01   154.6 3064.54
#Mann= 4 ,-1,0
       0      .1       0    58.1    .045       0   75.51      .1       0
     140     .06       0
Bank Sta=58.1,75.51
XS Rating Curve= 0 ,0
Exp/Cntr(USF)=0,0
Exp/Cntr=0.3,0.1

Type RM Length L Ch R = 1 ,18660   ,129.8,129.8,129.8
XS GIS Cut Line= 3
2200100.70175384592521.2849887592200098.01609064 592553.96055766
2200155.31023885 592664.07274875
#Sta/Elev= 30
       0 3056.88     7.9  3052.6    11.9 3051.14    15.9 3050.02      24 3048.31
    36.4 3044.57    42.7 3042.91    45.4 3042.07    49.9 3040.37    51.6 3039.93
    54.6 3039.47      59 3039.11    63.5 3039.19    66.4 3038.84   74.133036.437
    78.3 3035.44    81.3 3035.32   84.483036.439    87.2 3037.53    90.5 3039.54
    93.1 3039.61      95 3040.17   104.1 3043.65   113.1 3049.17   126.6 3056.81
   137.6 3064.13   144.6 3069.03   149.1 3071.87   152.4 3072.28 156.912 3072.21
#Mann= 4 ,-1,0
       0      .1       0   74.13    .045       0   84.48      .1       0
  122.79     .06       0
Bank Sta=74.13,84.48
XS Rating Curve= 0 ,0
Exp/Cntr(USF)=0,0
Exp/Cntr=0.3,0.1

Type RM Length L Ch R = 1 ,18530   ,138.2,138.2,138.2
XS GIS Cut Line= 3
2200046.33325678592504.7585044262199991.18374589592585.762055572
2199990.64272167592641.251802799
#Sta/Elev= 30
       0 3053.34    16.3  3051.1    19.9    3050    24.9 3048.88    27.8 3047.71
    29.5 3046.57    32.3 3044.23    34.4 3042.83    39.3 3040.29    42.2 3038.03
    44.1 3036.43    47.9 3031.76    48.9 3030.68    53.7 3026.79    56.6 3025.32
    58.6 3024.68    60.7 3024.58   64.073024.007    68.3 3023.27    73.1 3023.19
   78.723024.007    82.5 3025.42    87.6 3027.72      94 3029.38   101.4 3031.93
   109.4 3034.04   116.2 3037.71   137.4 3047.59   145.4 3050.26   153.5 3053.34
#Mann= 4 ,-1,0
       0      .1       0   64.07    .045       0   78.72      .1       0
     148     .06       0
Bank Sta=64.07,78.72
XS Rating Curve= 0 ,0
Exp/Cntr=0.3,0.1

Type RM Length L Ch R = 1 ,18392   ,141.1,141.1,141.1
XS GIS Cut Line= 3
2199867.63864578592489.0145610182199884.08096623592599.021514524
2199903.26367343592655.003700828
#Sta/Elev= 30
       0 3033.51     4.2 3031.25    12.3 3023.15    16.3 3019.88    20.4 3017.58
    28.1 3015.92    36.6 3014.82    42.8  3013.2    46.4 3012.75   50.83 3013.19
    60.8  3014.9    68.9  3017.7      77 3019.61    81.1 3019.33    85.1 3018.35
    93.2 3017.24    97.2 3017.38   105.3 3018.48   113.5 3019.05   117.7 3020.13
   125.6 3024.81   130.4 3027.27   134.7 3029.88   138.2 3032.57   143.1 3035.83
   151.6    3041     160 3045.67   163.4 3047.96   168.5 3052.07   170.4 3053.21
#Mann= 4 ,-1,0
       0      .1       0    42.8    .045       0   50.83      .1       0
  151.23     .06       0
Bank Sta=42.8,50.83
XS Rating Curve= 0 ,0
Exp/Cntr(USF)=0,0
Exp/Cntr=0.3,0.1

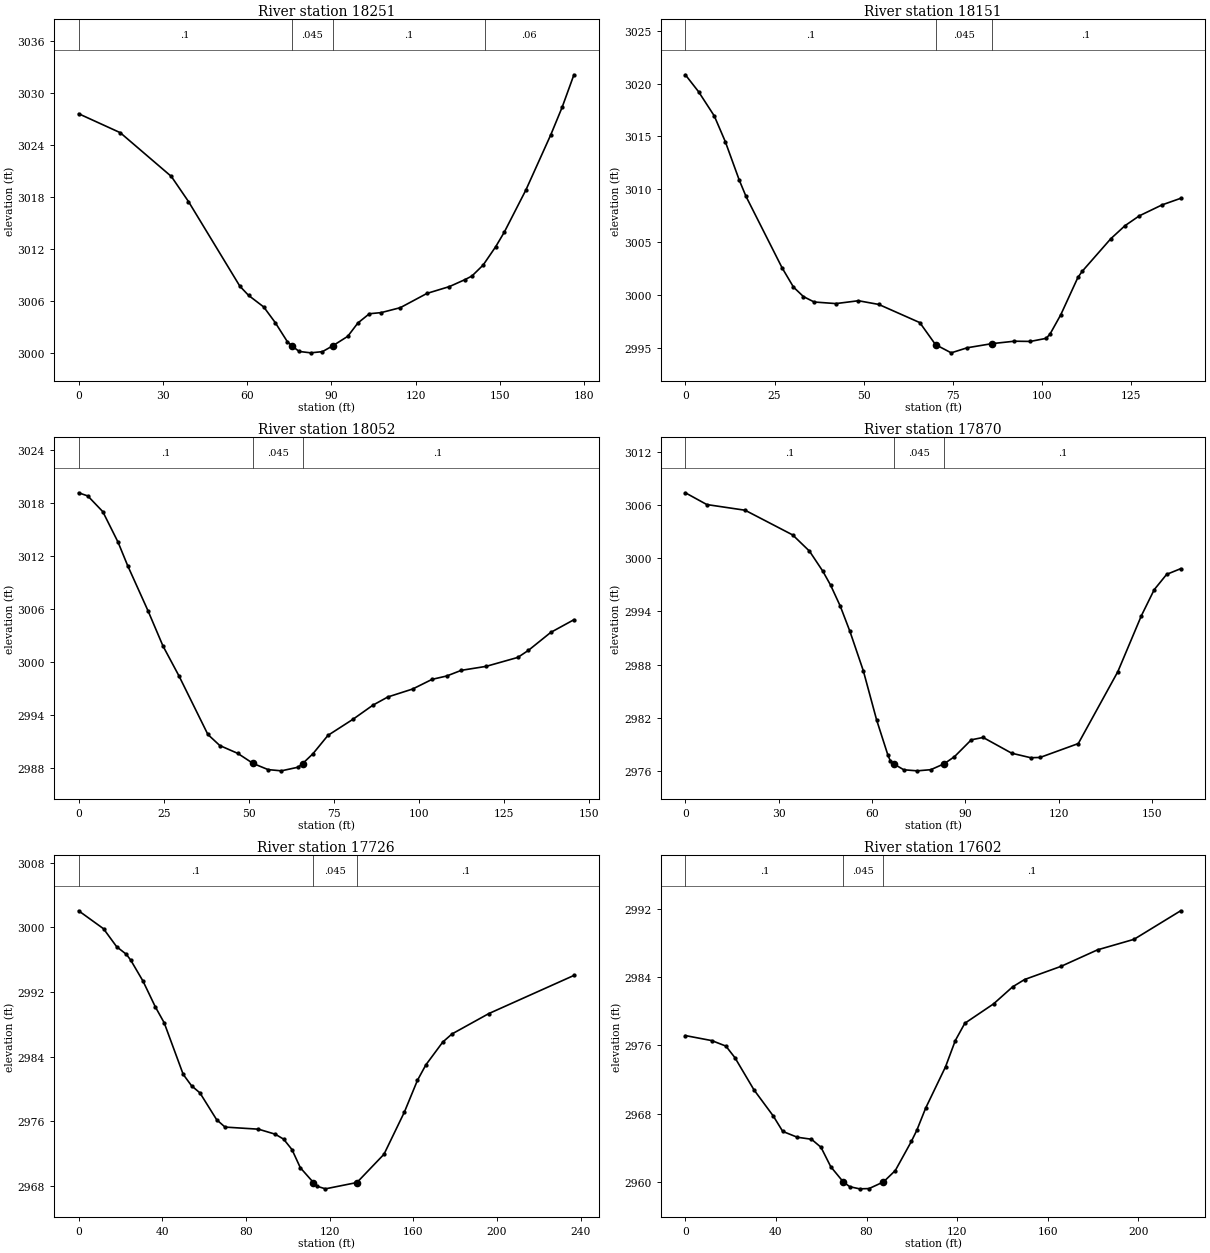
Type RM Length L Ch R = 1 ,18251   ,99.6,99.6,99.6
XS GIS Cut Line= 4
 2199799.3682695592511.4608861222199755.67036104592549.582948379
2199739.27853888592603.6946537492199741.68635995592665.415745817
#Sta/Elev= 30
       0 3027.61    14.8 3025.42      33 3020.36    39.1 3017.46    57.4 3007.67
    60.5 3006.61    65.9 3005.27      70 3003.46    74.3 3001.26   75.943000.777
    78.5 3000.13    82.6 2999.97    86.8 3000.11   90.423000.775    95.8 3001.88
    99.4 3003.42   103.5 3004.49   107.7 3004.62   114.5 3005.19     124 3006.84
     132 3007.63   137.5 3008.43     140 3008.85     144 3010.12   148.5 3012.26
   151.5 3013.91   159.2 3018.79   168.1  3025.2   172.1 3028.35   176.3 3032.11
#Mann= 4 ,-1,0
       0      .1       0   75.94    .045       0   90.42      .1       0
  144.53     .06       0
Bank Sta=75.94,90.42
XS Rating Curve= 0 ,0
Exp/Cntr=0.3,0.1

Type RM Length L Ch R = 1 ,18151   ,99.1,99.1,99.1
XS GIS Cut Line= 3
2199743.53827474592480.401916972 2199638.6206109 592530.12036215
 2199638.6206109592552.826423728
#Sta/Elev= 30
       0 3020.84     3.7 3019.24     8.1 3016.95    11.2 3014.51    15.1 3010.88
      17 3009.33    27.1 3002.58    30.3 3000.75    33.1 2999.85    36.1 2999.34
    42.2 2999.19    48.5 2999.46    54.2 2999.11    65.7 2997.39    70.1 2995.31
    74.5 2994.53      79 2995.01    85.9  2995.4    92.2 2995.63    96.7 2995.61
   101.1  2995.9   102.2 2996.31   105.2 2998.13     110 3001.66   111.2 3002.24
   119.2 3005.32   123.2 3006.56   127.2 3007.49   133.6 3008.53   138.8 3009.15
#Mann= 3 ,-1,0
       0      .1       0    70.1    .045       0    85.9      .1       0
Bank Sta=70.1,85.9
XS Rating Curve= 0 ,0
Exp/Cntr(USF)=0,0
Exp/Cntr=0.3,0.1

Type RM Length L Ch R = 1 ,18052   ,182.1,182.1,182.1
XS GIS Cut Line= 3
2199636.87301262592398.6999424482199596.61802708592485.346201268
2199614.60191672 592532.06333329
#Sta/Elev= 30
       0 3019.12     2.7 3018.76     7.1 3016.99    11.6 3013.53    14.4  3010.9
    20.4 3005.78    24.8  3001.8    29.5 2998.42      38  2991.8    41.5 2990.55
    46.8 2989.66    51.3 2988.52    55.7 2987.83    59.6 2987.69    64.5  2988.1
   65.85 2988.51    68.9 2989.63    73.3  2991.7    80.7 2993.53    86.5 2995.11
    90.9 2996.04    98.2 2996.94   103.9 2998.03   108.2 2998.41   112.5 2999.05
   119.8  2999.5   129.1 3000.51   132.2  3001.3   138.8 3003.34   145.6 3004.77
#Mann= 3 ,-1,0
       0      .1       0    51.3    .045       0   65.85      .1       0
Bank Sta=51.3,65.85
XS Rating Curve= 0 ,0
Exp/Cntr=0.3,0.1

Type RM Length L Ch R = 1 ,17870   ,144.6,144.6,144.6
XS GIS Cut Line= 3
2199472.40699889592360.351711878 2199423.5386482592477.957962423
2199426.22372242 592509.64183814
#Sta/Elev= 30
       0  3007.4     6.9 3006.07    19.2 3005.43    34.5 3002.64    39.9 3000.81
    44.2 2998.54    46.7 2996.96    49.8  2994.6    52.9 2991.75    57.2 2987.31
    61.5 2981.73    65.1 2977.79    65.9 2977.12   67.19 2976.75    70.2 2976.13
    74.5 2976.01    78.9 2976.14    83.2 2976.81    86.5 2977.61    91.9 2979.51
    95.7 2979.78   104.9    2978     111 2977.49     114 2977.52   126.3 2979.09
     139  2987.2   146.6 2993.54   150.7 2996.46   154.7 2998.19   159.2 2998.83
#Mann= 3 ,-1,0
       0      .1       0   67.19    .045       0    83.2      .1       0
Bank Sta=67.19,83.2
XS Rating Curve= 0 ,0
Exp/Cntr(USF)=0,0
Exp/Cntr=0.3,0.1

Type RM Length L Ch R = 1 ,17726   ,123.6,123.6,123.6
XS GIS Cut Line= 4
2199325.79529128592289.1090745622199302.16456317592333.288564947
2199302.56452945592455.8624622352199328.93707659592514.316675964
#Sta/Elev= 30
       0 3002.03    11.9 2999.81    18.2 2997.58    22.8 2996.65    24.9 2995.93
    30.8 2993.32    36.7 2990.13    40.9 2988.18      50 2981.79      54 2980.38
      58  2979.5      66 2976.18      70 2975.27      86 2975.01      94 2974.39
      98 2973.78     102 2972.49     106 2970.24  112.262968.411     114 2967.95
     118 2967.63  133.062968.412     146 2971.91   155.7  2977.1     162 2981.06
     166 2982.96   174.1 2985.79   178.5 2986.79   196.1 2989.31   236.8 2994.03
#Mann= 3 ,-1,0
       0      .1       0  112.26    .045       0  133.06      .1       0
Bank Sta=112.26,133.06
XS Rating Curve= 0 ,0
Exp/Cntr=0.3,0.1

Type RM Length L Ch R = 1 ,17602   ,138.6,138.6,138.6
XS GIS Cut Line= 3
 2199158.0561131592352.4943844082199205.61005586592490.897650655
2199259.55184168592539.161353756
#Sta/Elev= 30
       0 2977.16    11.7 2976.57    17.9 2975.93    21.9 2974.57    30.3 2970.81
    38.8 2967.76      43 2965.95    49.4 2965.27    55.7 2965.03    59.9 2964.09
    64.2 2961.82   69.73 2960.04    72.6 2959.48    76.9 2959.23    81.1 2959.26
   87.49 2960.04    92.7 2961.37    99.8 2964.78   102.2 2966.08   106.1 2968.67
   114.9 2973.52   119.2 2976.58   123.4  2978.6   136.1 2980.87   144.5 2982.86
   149.8 2983.72   165.9 2985.26     182 2987.19   198.1 2988.42   218.7 2991.76
#Mann= 3 ,-1,0
       0      .1       0   69.73    .045       0   87.49      .1       0
Bank Sta=69.73,87.49
XS Rating Curve= 0 ,0
Exp/Cntr(USF)=0,0
Exp/Cntr=0.3,0.1

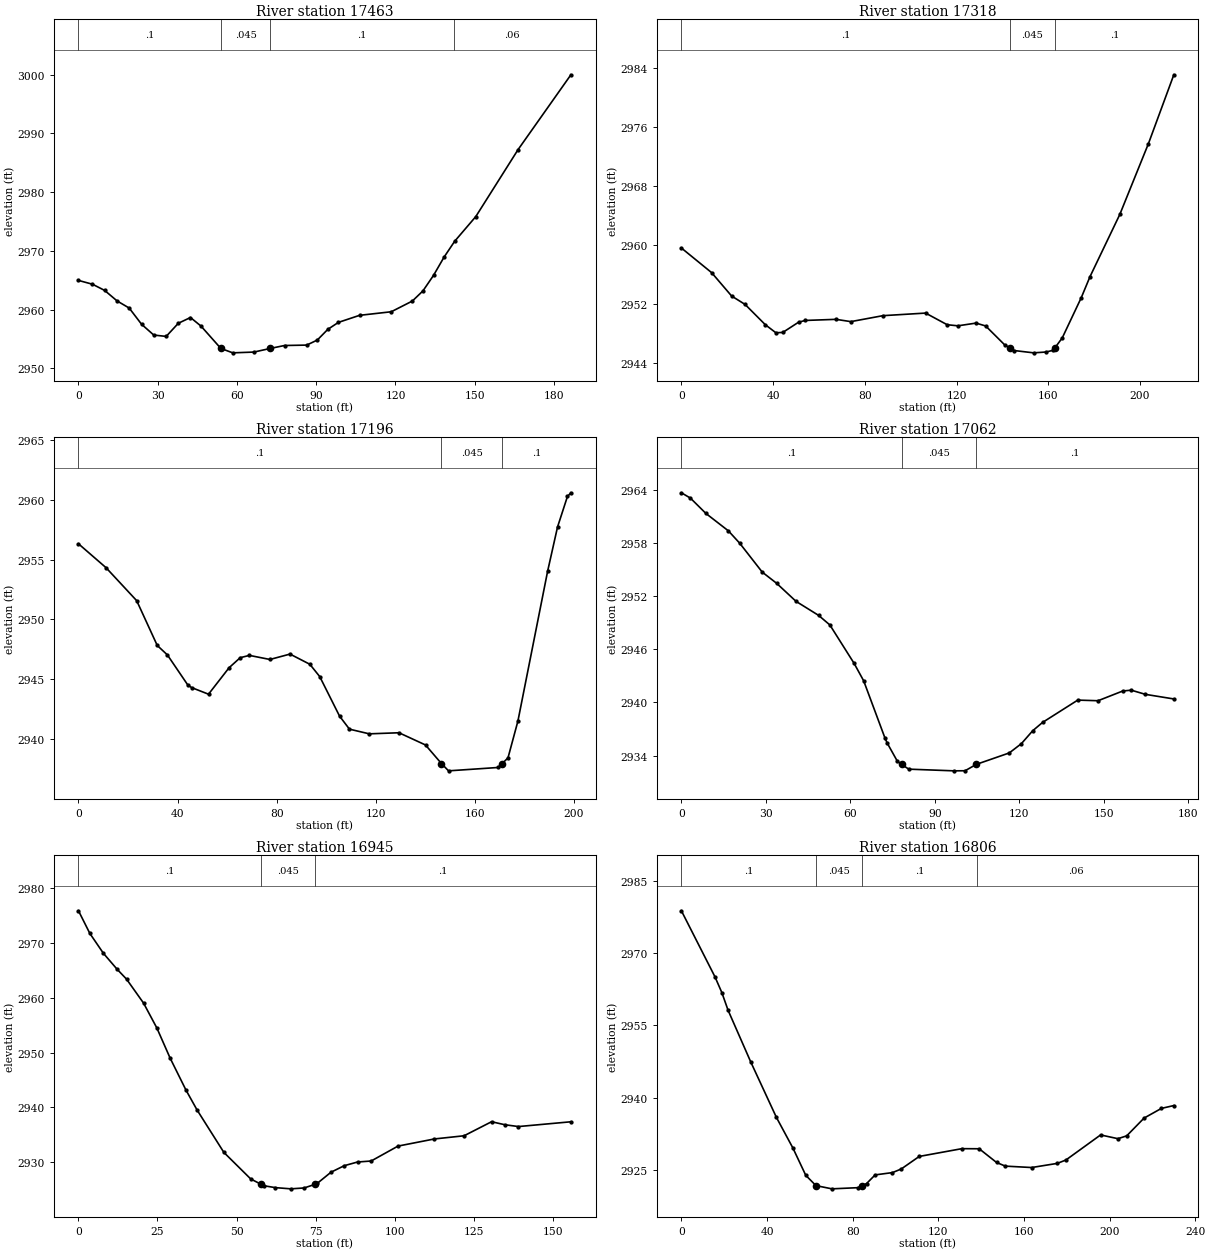
Type RM Length L Ch R = 1 ,17463   ,145.7,145.7,145.7
XS GIS Cut Line= 3
2199069.61057931592400.631149885 2199048.2305907592436.819600887
2199049.75790861592581.141842366
#Sta/Elev= 30
       0 2964.96     5.3 2964.31     9.9 2963.26    14.6 2961.47    19.2 2960.25
    23.9 2957.48    28.5 2955.65    33.2 2955.42    37.8 2957.66    42.4 2958.64
    46.4 2957.17    53.92953.367    58.4 2952.62    66.4 2952.75    72.6 2953.37
      78 2953.87    86.4 2953.94    90.4  2954.8    94.4 2956.63    98.4 2957.81
   106.4 2959.01   118.4 2959.62   126.4 2961.45   130.4 2963.18   134.4 2965.82
   138.4 2968.94   142.4 2971.63   150.4 2975.84   166.4 2987.25   186.4    3000
#Mann= 4 ,-1,0
       0      .1       0    53.9    .045       0    72.6      .1       0
  142.03     .06       0
Bank Sta=53.9,72.6
XS Rating Curve= 0 ,0
Exp/Cntr=0.3,0.1

Type RM Length L Ch R = 1 ,17318   ,121.3,121.3,121.3
XS GIS Cut Line= 3
2199019.52000542592370.426233468 2198910.3880814592436.050413694
2198885.37112871592519.802820502
#Sta/Elev= 30
       0 2959.56    13.2 2956.21    21.9 2953.04    27.8 2951.89    36.6 2949.14
    41.2 2948.05    44.2 2948.09    51.1 2949.48      54 2949.72    67.4 2949.87
    73.9 2949.56    87.9 2950.37   106.5 2950.72   115.9 2949.14   120.6 2948.99
   128.5 2949.36   132.7 2948.97     141  2946.4  143.112945.998   145.2 2945.63
   153.6 2945.32     159 2945.43   161.9 2945.65  162.892945.995   166.1 2947.35
   174.4 2952.82   178.2 2955.67   191.2 2964.12   203.7 2973.75214.7522 2983.09
#Mann= 3 ,-1,0
       0      .1       0  143.11    .045       0  162.89      .1       0
Bank Sta=143.11,162.89
XS Rating Curve= 0 ,0
Exp/Cntr(USF)=0,0
Exp/Cntr=0.3,0.1

Type RM Length L Ch R = 1 ,17196   ,134.1,134.1,134.1
XS GIS Cut Line= 3
2198994.93239383592348.1339679312198918.27112752592368.363688056
2198798.72987011592367.500443662
#Sta/Elev= 30
       0 2956.32    11.1 2954.33    23.5 2951.57    31.8 2947.83    35.9 2947.04
    44.2 2944.51    45.7 2944.31    52.5 2943.76    60.8 2945.97    65.3 2946.81
      69    2947    77.3 2946.66    85.4 2947.11    93.4 2946.26    97.4 2945.23
   105.4 2941.93   109.4 2940.84   117.4 2940.45   129.4 2940.54   140.1 2939.52
  146.552937.966   149.4 2937.36   169.4 2937.64  171.032937.966   173.4 2938.44
   177.4 2941.51   189.4 2954.03   193.4 2957.72   197.4 2960.27   198.8 2960.58
#Mann= 3 ,-1,0
       0      .1       0  146.55    .045       0  171.03      .1       0
Bank Sta=146.55,171.03
XS Rating Curve= 0 ,0
Exp/Cntr=0.3,0.1

Type RM Length L Ch R = 1 ,17062   ,117.5,117.5,117.5
XS GIS Cut Line= 2
2198968.88368975592239.5857095642198794.11230369 592242.46023894
#Sta/Elev= 30
       0 2963.65     3.2 2963.05     8.7 2961.32    16.7 2959.35    20.7 2957.96
    28.7  2954.7    33.8 2953.44    40.7  2951.4    48.7 2949.82    52.7 2948.74
    61.3 2944.41    64.7 2942.44    72.3 2935.95    73.1 2935.39    76.7 2933.34
   78.23    2933    80.7 2932.47    96.7 2932.28   100.7 2932.29   104.7 2933.01
   116.4  2934.3   120.7 2935.35   124.7  2936.8   128.2 2937.74   140.7 2940.26
   147.9 2940.19   156.7 2941.29   159.7 2941.38   164.7 2940.91   174.8 2940.39
#Mann= 3 ,-1,0
       0      .1       0   78.23    .045       0   104.7      .1       0
Bank Sta=78.23,104.7
XS Rating Curve= 0 ,0
Exp/Cntr(USF)=0,0
Exp/Cntr=0.3,0.1

Type RM Length L Ch R = 1 ,16945   ,138.6,138.6,138.6
XS GIS Cut Line= 2
2198832.08543251592089.7458751032198780.84432082592236.912163243
#Sta/Elev= 30
       0 2975.84     3.6 2971.71     7.9 2968.08    12.2  2965.2    15.2 2963.39
    20.6 2959.01    24.8 2954.48      29 2948.99      34 2943.18    37.5 2939.56
      46 2931.81    54.5 2926.97    57.82925.991    58.7 2925.73    62.3 2925.39
    67.2 2925.17    71.4 2925.33    74.82925.981    75.6 2926.19    79.9  2928.2
    84.1 2929.39    88.3 2930.06    92.6 2930.24   101.1 2932.96   112.6 2934.26
     122 2934.84   130.7  2937.4   134.9 2936.85   139.2 2936.52   155.8 2937.39
#Mann= 3 ,-1,0
       0      .1       0    57.8    .045       0    74.8      .1       0
Bank Sta=57.8,74.8
XS Rating Curve= 0 ,0
Exp/Cntr(USF)=0,0
Exp/Cntr=0.3,0.1

Type RM Length L Ch R = 1 ,16806   ,49.2,49.2,49.2
XS GIS Cut Line= 3
2198740.49835628592022.8192834612198696.88221865592061.126887504
2198669.93263465592230.962121436
#Sta/Elev= 30
       0 2978.73    15.7 2965.02    18.9 2961.76    21.8 2958.11    32.4 2947.38
    44.4 2935.87    52.1 2929.52    58.1 2923.87   62.85 2921.74    70.3 2921.07
    82.4 2921.31    84.5 2921.74    86.5 2922.17    90.5 2923.96    98.6 2924.44
   102.7 2925.19   111.1 2927.79     131  2929.4   139.1 2929.38   147.2 2926.54
   151.3 2925.78   163.6 2925.49   175.6 2926.35   179.6 2927.05   195.8 2932.25
   203.9 2931.47     208 2932.06   216.1 2935.74   224.2 2937.75     230 2938.34
#Mann= 4 ,-1,0
       0      .1       0   62.85    .045       0    84.5      .1       0
  138.05     .06       0
Bank Sta=62.85,84.5
XS Rating Curve= 0 ,0
Exp/Cntr(USF)=0,0
Exp/Cntr=0.3,0.1

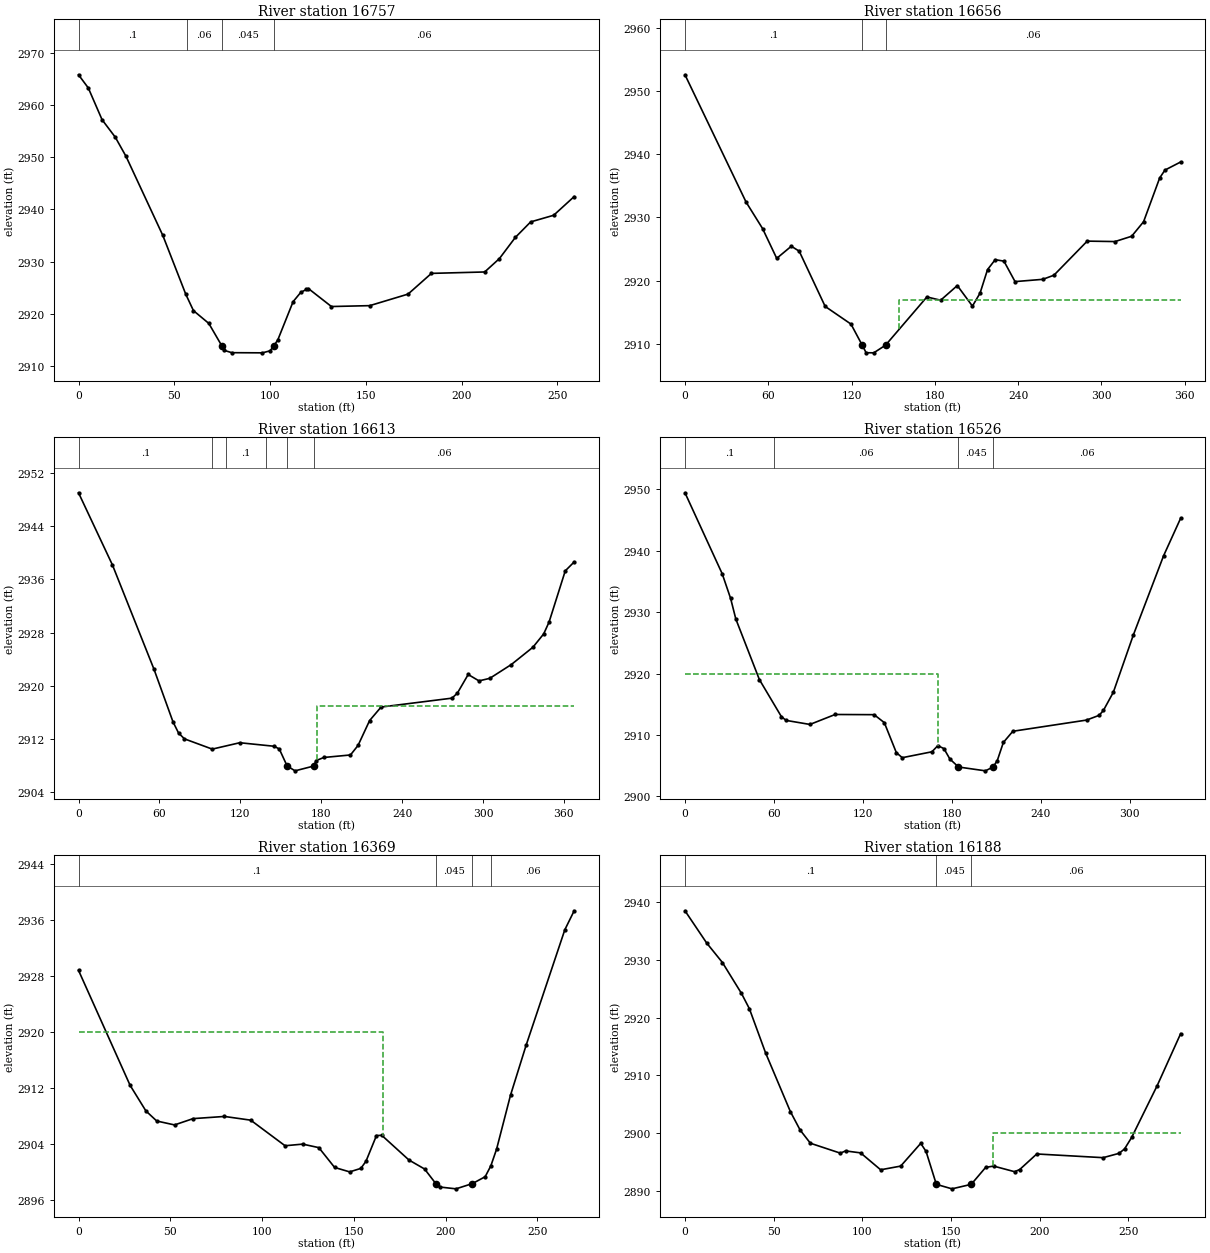
Type RM Length L Ch R = 1 ,16757   ,101.1,101.1,101.1
BEGIN DESCRIPTION:
Structure XS 4
END DESCRIPTION:
XS GIS Cut Line= 3
2198671.67255811591999.3175537962198646.43608361592025.600697126
2198643.30267438592247.822433387
#Sta/Elev= 30
       0 2965.77     5.1 2963.25    12.3 2957.16    19.2 2953.81    24.8 2950.14
      44    2935      56 2923.72      60 2920.59      68 2918.15   74.892913.793
      76 2912.99      80 2912.54      96 2912.51     100  2912.9  101.792913.797
     104 2914.97     112 2922.31     116 2924.09   118.9 2924.65     120 2924.82
     132 2921.38     152 2921.55     172 2923.76   184.2 2927.73     212    2928
   219.7 2930.57     228 2934.62     236 2937.59     248 2938.86   258.7 2942.44
#Mann= 4 ,-1,0
       0      .1       0   56.44     .06       0   74.89    .045       0
  101.79     .06       0
Bank Sta=74.89,101.79
XS Rating Curve= 0 ,0
Exp/Cntr=0.5,0.3

Type RM Length L Ch R = 1 ,16656   ,43.4,43.4,43.4
BEGIN DESCRIPTION:
Structure XS 3
END DESCRIPTION:
XS GIS Cut Line= 4
2198550.38970538591949.1822331172198505.13130705591997.424701661
2198624.49411582592108.8299898462198628.47287612592236.467677649
#Sta/Elev= 30
       0 2952.59      44 2932.44    55.9 2928.24    66.1 2923.52    76.6 2925.44
    82.3 2924.66     101 2915.91   119.6 2913.11   127.6 2909.81   130.5 2908.58
     136 2908.56   144.5 2909.77   174.3 2917.41   184.2 2916.89   196.2 2919.21
   207.1 2915.96   212.6 2918.02     218 2921.75   223.5 2923.31   229.8 2923.08
   237.8 2919.84   257.8  2920.2   265.8 2920.85   289.8 2926.25   309.8 2926.18
   321.8 2927.02   330.4 2929.32     342 2936.25   345.8  2937.5   357.1 2938.78
#Mann= 3 ,-1,0
       0      .1       0   127.6    .045       0   144.5     .06       0
#XS Ineff= 2 , 0
           117.8 2911.45   154.3            2917
Permanent Ineff=
       F       F
Bank Sta=127.6,144.5
XS Rating Curve= 0 ,0
Exp/Cntr(USF)=0,0
Exp/Cntr=0.5,0.3

Type RM Length L Ch R = 1 ,16613   ,86.7,86.7,86.7
BEGIN DESCRIPTION:
Structure XS 2
END DESCRIPTION:
XS GIS Cut Line= 4
2198537.52040485591947.3957240462198469.17036828592019.266845667
2198588.53317705592130.6721338522198591.43790766592235.755198263
#Sta/Elev= 30
       0 2949.05    25.2 2938.17      56 2922.48    70.1 2914.56    74.2 2912.89
    78.6 2912.01    99.2 2910.47   119.6 2911.43   145.1  2910.9   148.9 2910.49
   154.7 2907.94   160.6  2907.2   174.4 2907.92   176.2 2908.74   181.9 2909.21
   201.7 2909.59   207.3 2911.02   215.9 2914.77   224.4  2916.8     277 2918.14
     281  2918.9     289  2921.7     297 2920.74     305 2921.12     321  2923.2
     337  2925.8     345 2927.81     349  2929.6     361  2937.3   367.6 2938.64
#Mann= 6 ,-1,0
       0      .1       0   99.18     .06       0  109.18      .1       0
  139.18     .06       0   154.7    .045       0   174.4     .06       0
#XS Ineff= 2 , 0
          152.27    2909  176.83            2917
Permanent Ineff=
       F       F
Bank Sta=154.7,174.4
XS Rating Curve= 0 ,0
Exp/Cntr(USF)=0,0
Exp/Cntr=0.5,0.3

Type RM Length L Ch R = 1 ,16526   ,157,157,157
BEGIN DESCRIPTION:
Structure XS 1
END DESCRIPTION:
XS GIS Cut Line= 5
2198494.06669838591907.6625792842198446.73182282 591948.72550441
2198426.74922773592005.6945639282198437.69081854592158.876835182
2198405.86163291592207.054484358
#Sta/Elev= 30
       0 2949.41    25.1 2936.24    30.8 2932.21    34.3 2928.87    50.2 2919.01
      65    2913    68.2 2912.37    84.3 2911.71   101.3 2913.33   127.6  2913.3
   134.5    2912   142.6 2907.12   146.6  2906.3   166.6 2907.26   170.6 2908.26
   174.7 2907.78   178.7 2906.09  184.532904.784   202.7 2904.16  207.832904.785
   210.7 2905.83   214.8 2908.78   221.2  2910.6   270.9 2912.42   279.4 2913.19
   282.3 2913.99     289 2916.95   302.5 2926.27   322.9 2939.16   334.4 2945.26
#Mann= 4 ,-1,0
       0      .1       0      60     .06       0  184.53    .045       0
  207.83     .06       0
#XS Ineff= 2 , 0
        170.9208    2920
Permanent Ineff=
       F       F
Bank Sta=184.53,207.83
XS Rating Curve= 0 ,0
Exp/Cntr=0.3,0.1

Type RM Length L Ch R = 1 ,16369   ,181.2,181.2,181.2
XS GIS Cut Line= 3
2198397.90321561591859.475123185 2198298.4342083591990.774212832
2198262.62536567592089.745875103
#Sta/Elev= 30
       0 2928.76    28.1 2912.35    36.7  2908.7    42.6 2907.26    52.3  2906.7
    62.4  2907.6    79.5 2907.91    93.8 2907.38   112.5 2903.73   122.1 2903.96
   130.9 2903.46   139.5 2900.63   147.7    2900   153.8  2900.5   156.6 2901.53
   162.3 2905.19   165.2 2905.21     180 2901.69   188.5 2900.41  194.592898.333
   197.1 2897.83   205.6 2897.58  214.582898.333   221.5 2899.31   224.6 2900.87
   227.7 2903.23   235.3 2910.94   243.8 2918.07   264.9 2934.56269.9731 2937.26
#Mann= 4 ,-1,0
       0      .1       0  194.59    .045       0  214.58      .1       0
  224.72     .06       0
#XS Ineff= 2 , 0
        165.7829    2920
Permanent Ineff=
       F       F
Bank Sta=194.59,214.58
XS Rating Curve= 0 ,0
Exp/Cntr(USF)=0,0
Exp/Cntr=0.3,0.1

Type RM Length L Ch R = 1 ,16188   ,149.8,149.8,149.8
XS GIS Cut Line= 5
2198272.85628699591789.2772170042198244.70454752591840.898740891
2198192.43577625591892.8155312932198099.92959945 591945.03676013
2198084.36010143591982.618053327
#Sta/Elev= 30
       0  2938.5    12.2 2932.93    21.1 2929.54    31.8 2924.21    36.3 2921.54
    45.4 2913.91    59.4 2903.72    64.9 2900.52    70.7 2898.23    87.6 2896.51
    90.5  2896.9      99 2896.56   110.3 2893.63   121.6 2894.27   132.9 2898.21
   135.9 2896.81  141.69 2891.11   150.5 2890.33  161.362891.109   169.5 2894.05
     174 2894.27   185.8  2893.3   188.7 2893.68   198.3 2896.37   235.7 2895.73
   244.7 2896.48   247.8 2897.25   251.8 2899.24   266.2 2908.22   279.4 2917.21
#Mann= 3 ,-1,0
       0      .1       0  141.69    .045       0  161.36     .06       0
#XS Ineff= 2 , 0
                           173.9            2900
Permanent Ineff=
       F       F
Bank Sta=141.69,161.36
XS Rating Curve= 0 ,0
Exp/Cntr=0.3,0.1