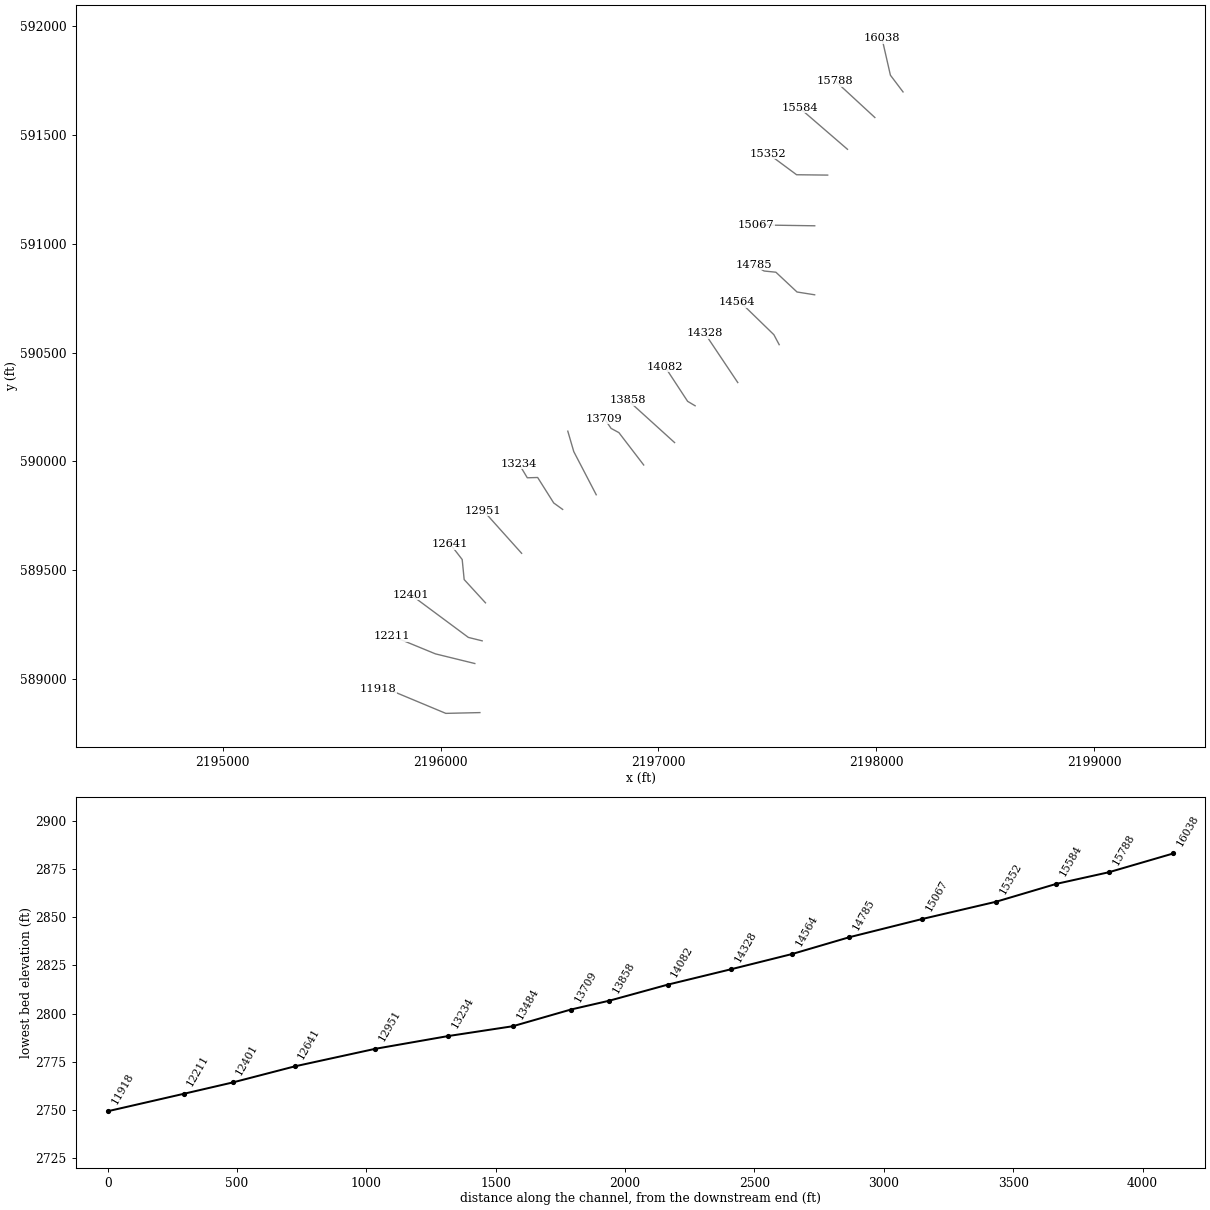
HEC-RAS study SUGARCK.prj: SUGARCK

--- SUGARCK.g01 (geometry) --- (continued)

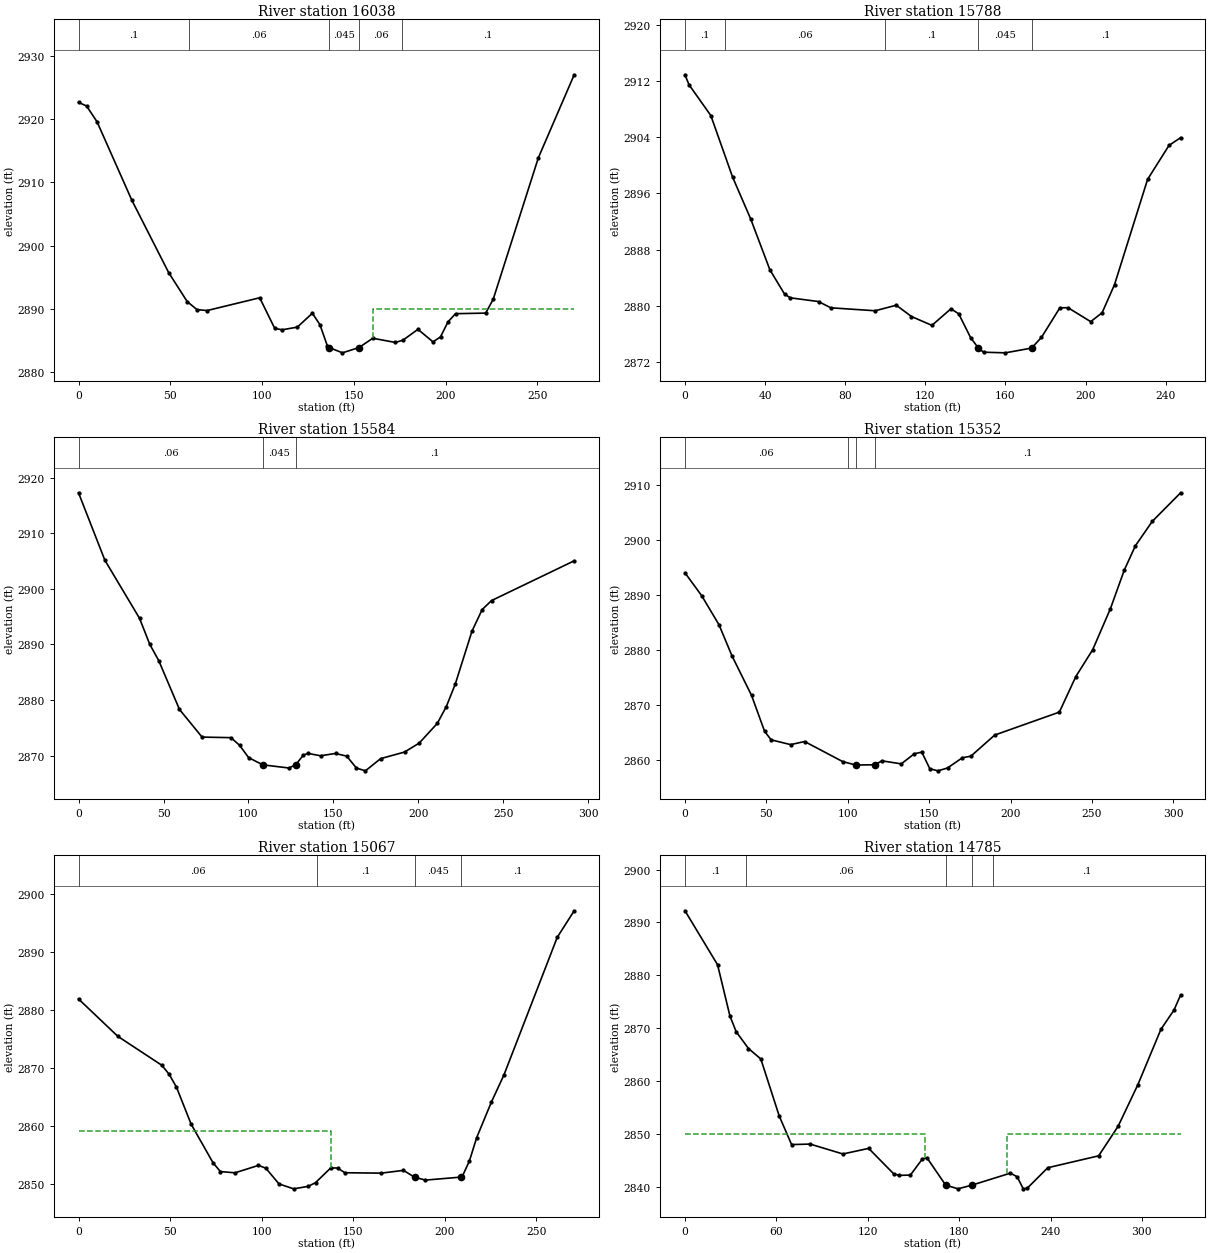
Type RM Length L Ch R = 1 ,16038   ,249.8,249.8,249.8
XS GIS Cut Line= 3
2198123.07531906591697.9755292582198065.05173147591774.787707123
2198026.38420483591944.174861181
#Sta/Elev= 30
       0 2922.61     4.4 2922.03    10.1 2919.54    29.1 2907.13    49.1 2895.75
    59.2 2891.17    64.5 2889.91      70 2889.75    98.7 2891.77   106.9 2886.93
     111 2886.72   119.2 2887.14   127.4 2889.33   131.5 2887.53   135.6 2884.15
  136.492883.921   143.8 2883.08  152.832883.921   160.3 2885.38   172.6 2884.72
   176.7 2885.07   184.9 2886.79   193.1 2884.81   197.2  2885.6   201.3 2887.98
   205.4 2889.26   221.8 2889.35   225.9 2891.53   250.5 2913.86270.0091 2926.96
#Mann= 5 ,-1,0
       0      .1       0      60     .06       0  136.49    .045       0
  152.83     .06       0  176.26      .1       0
#XS Ineff= 1 ,-1
 160.663 270.009    2890
Permanent Ineff=
       F
Bank Sta=136.49,152.83
XS Rating Curve= 0 ,0
Exp/Cntr(USF)=0,0
Exp/Cntr=0.3,0.1

Type RM Length L Ch R = 1 ,15788   ,203.8,203.8,203.8
XS GIS Cut Line= 2
2197993.67356997591580.3859411382197811.89353866591748.371215749
#Sta/Elev= 30
       0 2912.89       2 2911.48    12.9 2907.09    23.8 2898.31    32.8 2892.38
    42.4 2885.13    49.7 2881.68    52.6 2881.14    66.7 2880.61    72.8 2879.72
      95  2879.3   105.5 2880.09   113.1 2878.48   123.3 2877.22   132.8 2879.58
   136.7 2878.86   142.6 2875.49  146.512873.988   149.1  2873.4     160 2873.31
  173.09 2873.99     178 2875.51   187.2 2879.72   191.3 2879.73   202.6 2877.75
   208.3 2879.02   214.5 2883.03     231    2898   241.7 2902.84   247.5 2903.94
#Mann= 5 ,-1,0
       0      .1       0      20     .06       0     100      .1       0
  146.51    .045       0  173.09      .1       0
Bank Sta=146.51,173.09
XS Rating Curve= 0 ,0
Exp/Cntr=0.3,0.1

Type RM Length L Ch R = 1 ,15584   ,231.9,231.9,231.9
XS GIS Cut Line= 2
2197867.92237879591434.3416137922197647.21889649591624.929204404
#Sta/Elev= 30
       0 2917.27    15.5 2905.14    35.9 2894.69    41.9 2890.02    47.2 2887.08
    59.4 2878.29    72.7 2873.32    89.7 2873.22    94.8 2871.83   100.1 2869.62
  108.41 2868.33   123.8 2867.76  127.84 2868.37   132.3 2870.09   135.1 2870.38
   142.4 2869.96   151.2 2870.38   157.8 2869.89   163.5 2867.75   168.8 2867.25
   177.7 2869.44   191.8 2870.63   200.4 2872.23   211.1 2875.79   216.4 2878.82
   221.6 2882.81   231.5 2892.39   237.5 2896.27     243 2897.88   291.6 2905.03
#Mann= 3 ,-1,0
       0     .06       0  108.41    .045       0  127.84      .1       0
Bank Sta=108.41,127.84
XS Rating Curve= 0 ,0
Exp/Cntr=0.3,0.1

Type RM Length L Ch R = 1 ,15352   ,285.2,285.2,285.2
XS GIS Cut Line= 3
 2197777.1103866591315.7818151692197634.25905802591317.432253879
2197504.39352945 591413.73239799
#Sta/Elev= 30
       0 2894.03    10.2  2889.9    20.9 2884.59    28.9 2878.91    40.9 2871.74
    48.9 2865.21    52.9 2863.66    64.9 2862.79    73.5 2863.35    96.9  2859.7
   104.9 2859.08   116.9 2859.12   120.9 2859.84   132.9 2859.29   140.9 2861.13
   145.5 2861.42   150.4 2858.41   155.4 2858.02   161.3 2858.54   170.4  2860.4
   175.6 2860.68   190.3 2864.53     230  2868.7   240.1 2875.16   250.5 2880.06
   261.4 2887.54   269.9 2894.54   276.7 2898.95   287.1  2903.4   304.5 2908.59
#Mann= 4 ,-1,0
       0     .06       0     100      .1       0   104.9    .045       0
   116.9      .1       0
Bank Sta=104.9,116.9
XS Rating Curve= 0 ,0
Exp/Cntr=0.3,0.1

Type RM Length L Ch R = 1 ,15067   ,281.6,281.6,281.6
XS GIS Cut Line= 2
2197717.66963121591082.8770650722197446.97118256591086.919523672
#Sta/Elev= 30
       0 2881.87    21.5 2875.41    45.5 2870.42    49.5 2868.87    53.5 2866.64
    61.5 2860.26    73.5 2853.57    77.5 2852.06    85.5 2851.85    98.3 2853.13
   102.3 2852.65   109.5 2849.93   117.5 2849.08   125.5 2849.51   129.5 2850.16
   137.8  2852.7   141.5 2852.67   145.5 2851.86   165.3 2851.79   177.5 2852.27
  183.59 2851.08   189.5 2850.59   208.7  2851.1   209.5 2851.14   213.5 2853.89
   217.5 2857.94   225.5 2864.05   232.4 2868.77   261.5 2892.52270.7286  2897.1
#Mann= 4 ,-1,0
       0     .06       0     130      .1       0  183.59    .045       0
   208.7      .1       0
#XS Ineff= 2 , 0
           137.8    2859
Permanent Ineff=
       F       F
Bank Sta=183.59,208.7
XS Rating Curve= 0 ,0
Exp/Cntr=0.3,0.1

Type RM Length L Ch R = 1 ,14785   ,221.3,221.3,221.3
XS GIS Cut Line= 5
2197717.31635906590765.8113086372197636.26753829590778.705439214
2197539.25455585 590869.578359472197485.22200867590875.104415431
2197436.71551745590903.348701457
#Sta/Elev= 30
       0 2892.21    21.4    2882    29.5 2872.34    33.6 2869.35    41.7 2866.17
    49.8 2864.19    61.9 2853.39      70 2848.01    82.2  2848.1   103.7 2846.23
   120.6 2847.29     137 2842.49   140.5 2842.19     148 2842.24   155.9  2845.3
   158.9 2845.51  171.152840.345   179.3 2839.64   188.6 2840.36   213.7 2842.61
   218.1 2841.92   222.1 2839.65   224.7 2839.75   238.2 2843.63   271.6 2845.88
   284.4 2851.47   297.3 2859.29   312.5  2869.8   321.1 2873.45325.4392  2876.3
#Mann= 5 ,-1,0
       0      .1       0      40     .06       0  171.15    .045       0
   188.6     .06       0  202.07      .1       0
#XS Ineff= 2 , 0
           157.5    2850  211.23            2850
Permanent Ineff=
       F       F
Bank Sta=171.15,188.6
XS Rating Curve= 0 ,0
Exp/Cntr(USF)=0,0
Exp/Cntr=0.3,0.1

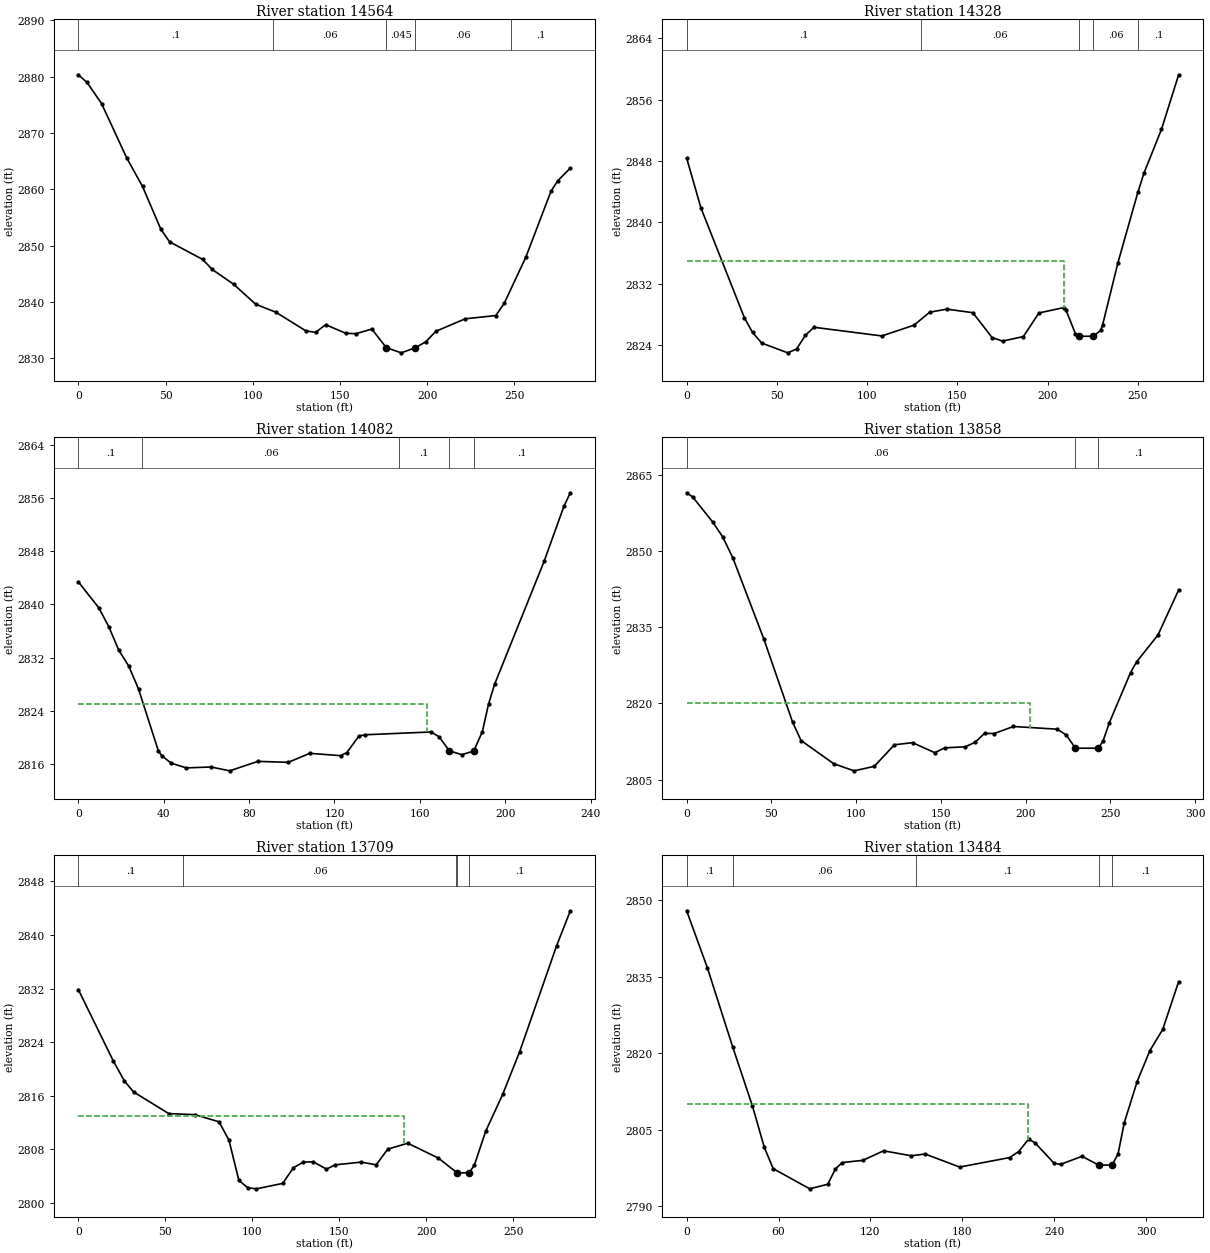
Type RM Length L Ch R = 1 ,14564   ,236.2,236.2,236.2
XS GIS Cut Line= 4
2197554.41141709 590536.668488852197530.02231216590582.467354706
2197389.29876342590719.304899046 2197357.9911257590732.303526918
#Sta/Elev= 30
       0 2880.35       5 2878.99    13.3 2875.24    27.8 2865.54    36.8  2860.5
    47.3  2852.9    52.3 2850.66    71.2 2847.54    76.8 2845.74    89.1  2843.1
   101.7 2839.56   113.2 2838.15   130.4 2834.84   136.1 2834.55   141.8 2835.93
   153.3  2834.4   159.1 2834.32   168.3 2835.15  176.612831.831   185.2 2830.92
  193.262831.831   199.2 2832.88     205 2834.75   221.8 2836.97   239.4 2837.55
   244.2 2839.73   256.6 2847.93     271 2859.64   274.9 2861.51   282.1 2863.77
#Mann= 5 ,-1,0
       0      .1       0  111.89     .06       0  176.61    .045       0
  193.26     .06       0  248.17      .1       0
Bank Sta=176.61,193.26
XS Rating Curve= 0 ,0
Exp/Cntr=0.3,0.1

Type RM Length L Ch R = 1 ,14328   ,245.5,245.5,245.5
XS GIS Cut Line= 2
2197364.26458302590362.5884738682197212.78252878590589.124588229
#Sta/Elev= 30
       0 2848.38     7.9 2841.89      32 2827.57    36.5 2825.66    41.6 2824.28
      56 2823.01    60.9 2823.51    65.7 2825.27    70.5 2826.34   108.1 2825.21
   125.9 2826.61   134.6  2828.3   144.1  2828.7   158.5 2828.24   169.2    2825
     175 2824.54   186.5 2825.13   195.1  2828.2   208.8  2828.9     210 2828.63
   215.3 2825.52  217.08 2825.17  225.31 2825.17   229.3 2825.94   230.4 2826.66
   238.9 2834.77   249.9  2843.9   253.3 2846.42     263 2852.12   272.5 2859.22
#Mann= 5 ,-1,0
       0      .1       0     130     .06       0  217.08    .045       0
  225.31     .06       0     250      .1       0
#XS Ineff= 2 , 0
          208.85    2835
Permanent Ineff=
       F       F
Bank Sta=217.08,225.31
XS Rating Curve= 0 ,0
Exp/Cntr=0.3,0.1

Type RM Length L Ch R = 1 ,14082   ,224.9,224.9,224.9
XS GIS Cut Line= 3
2197168.43100871590255.9083098542197134.00513039590276.336571411
 2197029.6744319590435.686636345
#Sta/Elev= 30
       0  2843.4     9.6 2839.48    14.3 2836.64    18.9 2833.15    23.6 2830.75
    28.2 2827.29    37.5    2818    39.1 2817.28    43.4 2816.17    50.6 2815.44
    62.2 2815.58    70.9    2815    84.1 2816.42    98.4 2816.28   108.4 2817.63
   122.9 2817.28   125.8 2817.74   131.5 2820.24   134.4 2820.42   165.3 2820.84
   169.1 2820.09  173.83    2818   179.7 2817.43  185.28 2817.98   189.3  2820.9
   192.2 2825.06   195.1 2828.07   218.2 2846.45   227.5 2854.74   230.5 2856.77
#Mann= 5 ,-1,0
       0      .1       0      30     .06       0  150.03      .1       0
  173.83    .045       0  185.28      .1       0
#XS Ineff= 2 , 0
          163.31    2825
Permanent Ineff=
       F       F
Bank Sta=173.83,185.28
XS Rating Curve= 0 ,0
Exp/Cntr=0.3,0.1

Type RM Length L Ch R = 1 ,13858   ,148.7,148.7,148.7
XS GIS Cut Line= 2
2197074.18895879590086.8450255562196859.14692908590281.827399776
#Sta/Elev= 30
       0 2861.52     3.5 2860.72    15.4 2855.75    21.3 2852.81    27.3 2848.65
    45.6 2832.65    62.5 2816.32    67.5 2812.69    86.8 2808.11    98.8 2806.71
   110.7  2807.6   122.6 2811.85   133.3 2812.26   146.4 2810.29   152.3 2811.24
   164.5 2811.45   170.2 2812.35   175.8 2814.09   181.5 2814.07   192.8 2815.45
   218.7 2814.92     224 2813.76   229.4 2811.17  242.93 2811.17   245.7  2812.6
   249.4 2816.18   261.9 2826.06   265.5  2828.2   278.1 2833.48   290.3 2842.37
#Mann= 3 ,-1,0
       0     .06       0   229.4    .045       0  242.93      .1       0
#XS Ineff= 2 , 0
           202.5    2820
Permanent Ineff=
       F       F
Bank Sta=229.4,242.93
XS Rating Curve= 0 ,0
Exp/Cntr=0.3,0.1

Type RM Length L Ch R = 1 ,13709   ,224.9,224.9,224.9
XS GIS Cut Line= 4
2196932.30617181589983.9096462032196818.41415845590132.615812127
2196782.60531582590152.0122685522196751.69586887590197.358100134
#Sta/Elev= 30
       0 2831.85      20 2821.26    26.5 2818.21    31.8 2816.57      52 2813.35
    67.1 2813.19    80.9 2812.12    86.6  2809.4    92.3  2803.4    97.3  2802.3
   102.4 2802.12   117.5 2802.93   123.7 2805.27   129.4 2806.11   135.1 2806.15
   142.7 2805.06   147.7  2805.7   162.8 2806.11   171.3  2805.7   177.9 2808.04
   189.4 2808.93   207.1  2806.7  217.91 2804.49   224.8 2804.53   227.7 2805.64
   234.3 2810.75     244  2816.2   253.7 2822.53     275 2838.37282.9127 2843.61
#Mann= 5 ,-1,0
       0      .1       0      60     .06       0  217.31      .1       0
  217.91    .045       0   224.8      .1       0
#XS Ineff= 2 , 0
          187.21    2813
Permanent Ineff=
       F       F
Bank Sta=217.91,224.8
XS Rating Curve= 0 ,0
Exp/Cntr(USF)=0,0
Exp/Cntr=0.3,0.1

Type RM Length L Ch R = 1 ,13484   ,250.4,250.4,250.4
XS GIS Cut Line= 3
2196714.43483365589847.0387769232196611.36688069590045.274359228
2196583.88972275590139.197345213
#Sta/Elev= 30
       0 2847.97    13.6 2836.74      30 2821.34      43 2809.66    50.7  2801.6
    56.5 2797.41    80.4 2793.45    92.2 2794.36    97.1 2797.33   101.6  2798.6
   115.1 2799.04   128.6 2800.91   146.7 2799.93   155.7 2800.28   178.3 2797.72
   210.9 2799.58   216.8 2800.76   223.3 2803.17   227.5 2802.48     240 2798.45
   244.2 2798.25   258.2 2799.83   269.2 2798.09  277.86 2798.13   281.7 2800.26
   285.8 2806.42   294.2 2814.48   302.5 2820.55   310.9  2824.7   321.3 2834.08
#Mann= 5 ,-1,0
       0      .1       0      30     .06       0     150      .1       0
   269.2    .045       0  277.86      .1       0
#XS Ineff= 2 , 0
          222.76    2810
Permanent Ineff=
       F       F
Bank Sta=269.2,277.86
XS Rating Curve= 0 ,0
Exp/Cntr=0.3,0.1

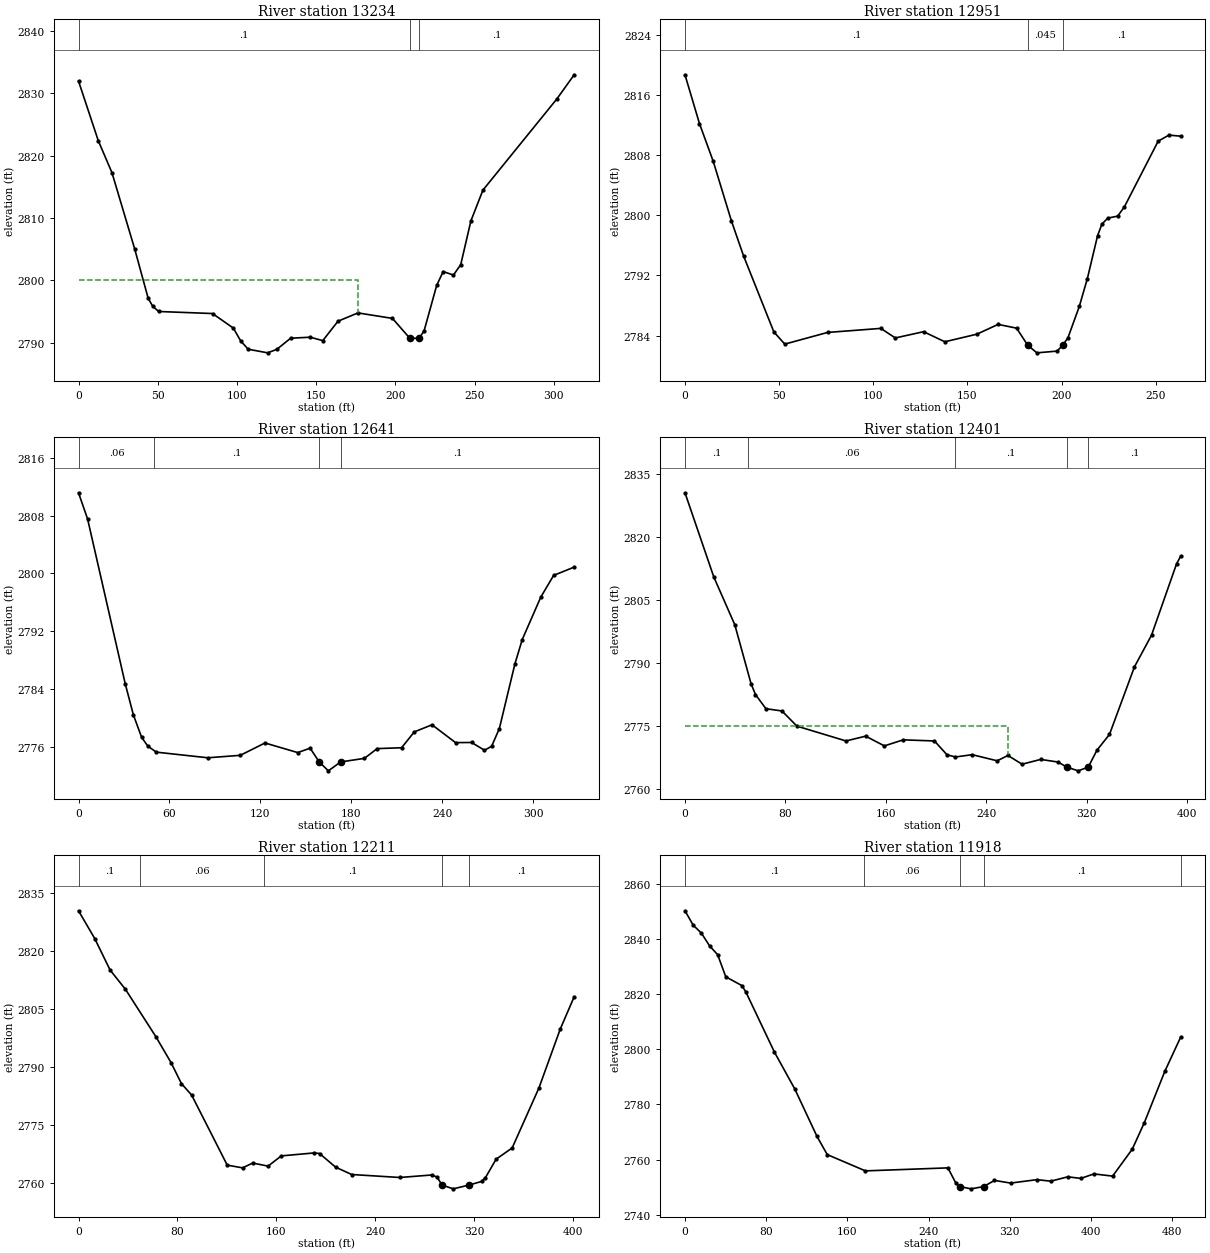
Type RM Length L Ch R = 1 ,13234   ,282.3,282.3,282.3
XS GIS Cut Line= 5
2196560.25085577589779.762700354 2196519.2136856589809.369278086
2196445.46149551589926.4186122982196397.95483348589925.019533774
2196358.63920713589990.531318375
#Sta/Elev= 30
       0 2831.98    12.5 2822.39    21.1 2817.28    35.5 2804.99      44 2797.08
    46.9  2795.8    50.6 2794.98    84.6 2794.65    97.7 2792.32   102.4 2790.25
   107.1 2788.92   119.4 2788.34   125.2  2788.9   133.9 2790.69   146.3 2790.85
   154.2  2790.3   163.8 2793.42   176.4 2794.75   198.2 2793.87  209.12 2790.69
  215.08 2790.67   218.2 2791.91   226.1 2799.16   230.2 2801.39   236.7 2800.83
   241.3 2802.51   247.7 2809.52   255.3 2814.47     302 2829.12   312.9 2832.99
#Mann= 3 ,-1,0
       0      .1       0  209.12    .045       0  215.08      .1       0
#XS Ineff= 2 , 0
          176.36    2800
Permanent Ineff=
       F       F
Bank Sta=209.12,215.08
XS Rating Curve= 0 ,0
Exp/Cntr=0.3,0.1

Type RM Length L Ch R = 1 ,12951   ,310.3,310.3,310.3
XS GIS Cut Line= 2
2196371.93162945589578.0348392512196196.24206885589774.040272526
#Sta/Elev= 30
       0 2818.67     7.7 2812.18      15 2807.17    24.7 2799.22    31.1  2794.6
    47.2 2784.49      53 2782.87    75.7 2784.42     104 2784.96   111.7 2783.69
   126.7 2784.52     138 2783.18     155 2784.19   166.3 2785.49   176.1 2784.99
  182.042782.714   186.9 2781.71   197.6 2781.94   200.62782.712   203.4 2783.73
   209.4 2787.87   213.7 2791.59   219.1 2797.27   221.4 2798.81   224.5 2799.62
   229.8 2799.88   233.4 2801.14   251.3 2809.85     257 2810.65263.2203 2810.51
#Mann= 3 ,-1,0
       0      .1       0  182.04    .045       0   200.6      .1       0
Bank Sta=182.04,200.6
XS Rating Curve= 0 ,0
Exp/Cntr=0.3,0.1

Type RM Length L Ch R = 1 ,12641   ,240.3,240.3,240.3
XS GIS Cut Line= 4
2196205.97005796589350.4748159682196108.07763442  589457.4313528
2196099.01352112589549.5227438352196044.26627685589620.222827503
#Sta/Elev= 30
       0 2811.16       6 2807.52    30.8 2784.71    36.2 2780.38    41.6 2777.29
    45.7 2776.06    51.3 2775.22    85.3 2774.44   106.7 2774.78     123 2776.49
   144.6 2775.16   152.8 2775.77  158.75 2773.87   164.8 2772.63   172.9 2773.86
   188.6 2774.36     197 2775.71   213.1 2775.83   221.5 2778.03   233.2 2779.01
   248.7 2776.54   259.3 2776.56   267.8 2775.48   272.5 2776.03   277.6 2778.49
   287.9 2787.48   292.7 2790.82   304.9 2796.69   313.4 2799.71326.9472 2800.86
#Mann= 4 ,-1,0
       0     .06       0      50      .1       0  158.75    .045       0
   172.9      .1       0
Bank Sta=158.75,172.9
XS Rating Curve= 0 ,0
Exp/Cntr(USF)=0,0
Exp/Cntr=0.3,0.1

Type RM Length L Ch R = 1 ,12401   ,189.4,189.4,189.4
XS GIS Cut Line= 3
2196190.73671935589175.9022740682196127.37615308589191.617224293
2195862.66999254589388.165798266
#Sta/Elev= 30
       0  2830.5      23 2810.42    39.7 2799.07    52.7 2784.98    56.2 2782.44
    64.5 2779.07    77.3 2778.53    89.2 2774.92   128.3 2771.39     144 2772.53
   158.9 2770.21   173.9 2771.65   198.8 2771.39   208.8  2768.1   215.5 2767.57
   228.9 2768.12   248.8 2766.66   257.4 2767.93   268.6 2765.85   283.5 2766.99
   297.4 2766.36  304.122765.178   313.4 2764.27  321.432765.178   328.3 2769.18
   338.3 2772.94   358.2 2789.04   371.8 2796.58   391.8 2813.61     395 2815.37
#Mann= 5 ,-1,0
       0      .1       0      50     .06       0  215.28      .1       0
  304.12    .045       0  321.43      .1       0
#XS Ineff= 2 , 0
           257.4    2775
Permanent Ineff=
       F       F
Bank Sta=304.12,321.43
XS Rating Curve= 0 ,0
Exp/Cntr=0.3,0.1

Type RM Length L Ch R = 1 ,12211   ,293.1,293.1,293.1
XS GIS Cut Line= 3
2196156.94544246589071.7036314952195976.18429118589116.025520274
2195777.81109096589197.682990184
#Sta/Elev= 30
       0 2830.38    13.1  2823.2    25.5 2815.05    37.9 2810.06    62.6 2797.74
    74.9    2791    83.2 2785.61    91.4 2782.68   120.2 2764.52   132.6 2763.81
   140.8 2765.06   153.2 2764.26   163.9 2766.91   190.5 2767.68   194.8 2767.53
   207.8 2763.99   220.8 2762.09   259.7 2761.32   285.6 2761.97   289.9  2761.4
  293.762759.355   302.9 2758.38  315.442759.354   325.8 2760.29   328.9 2761.28
   337.5 2766.05   350.5 2768.97   372.1 2784.48   389.4 2799.79   400.6 2808.11
#Mann= 5 ,-1,0
       0      .1       0      50     .06       0     150      .1       0
  293.76    .045       0  315.44      .1       0
Bank Sta=293.76,315.44
XS Rating Curve= 0 ,0
Exp/Cntr=0.3,0.1

Type RM Length L Ch R = 1 ,11918   ,224.7,224.7,224.7
XS GIS Cut Line= 4
2196180.31871898 588846.198393952196023.78244643 588842.61036738
2195780.95647845588944.0339643652195713.21093858 588955.40832862
#Sta/Elev= 30
       0  2850.3     8.1 2845.07    16.1 2842.23    24.2 2837.58    32.2 2834.35
    40.2 2826.34    56.2 2823.12    60.2 2820.68    88.2 2798.96   108.2 2785.62
   130.1 2768.38   140.2 2761.79   177.8 2755.88   259.1 2756.97     267 2751.39
  270.722750.189   281.9 2749.36  294.372750.189     305 2752.42   320.9 2751.45
   346.9  2752.7   360.4 2752.14   377.2 2753.72   390.2 2753.15   402.9 2754.78
   421.4 2753.98   440.8 2763.78   452.7 2773.42   472.9 2792.06   488.4 2804.38
#Mann= 5 ,-1,0
       0      .1       0  176.58     .06       0  270.72    .045       0
  294.37      .1       0  488.43     .08       0
Bank Sta=270.72,294.37
XS Rating Curve= 0 ,0
Exp/Cntr=0.3,0.1