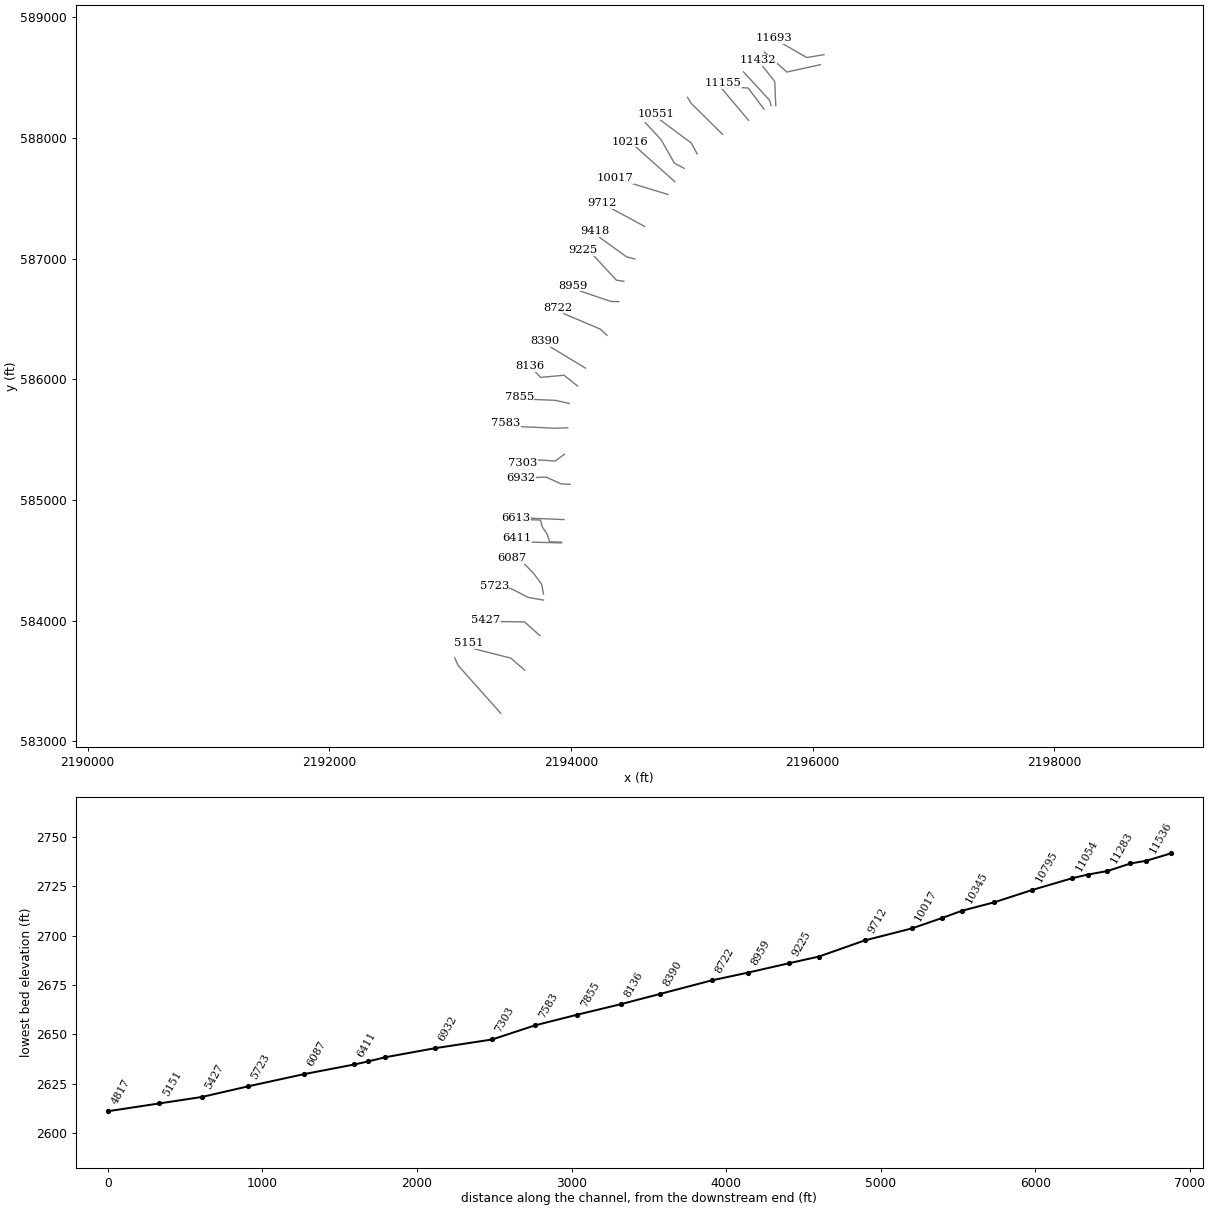
HEC-RAS study SUGARCK.prj: SUGARCK

--- SUGARCK.g01 (geometry) --- (continued)

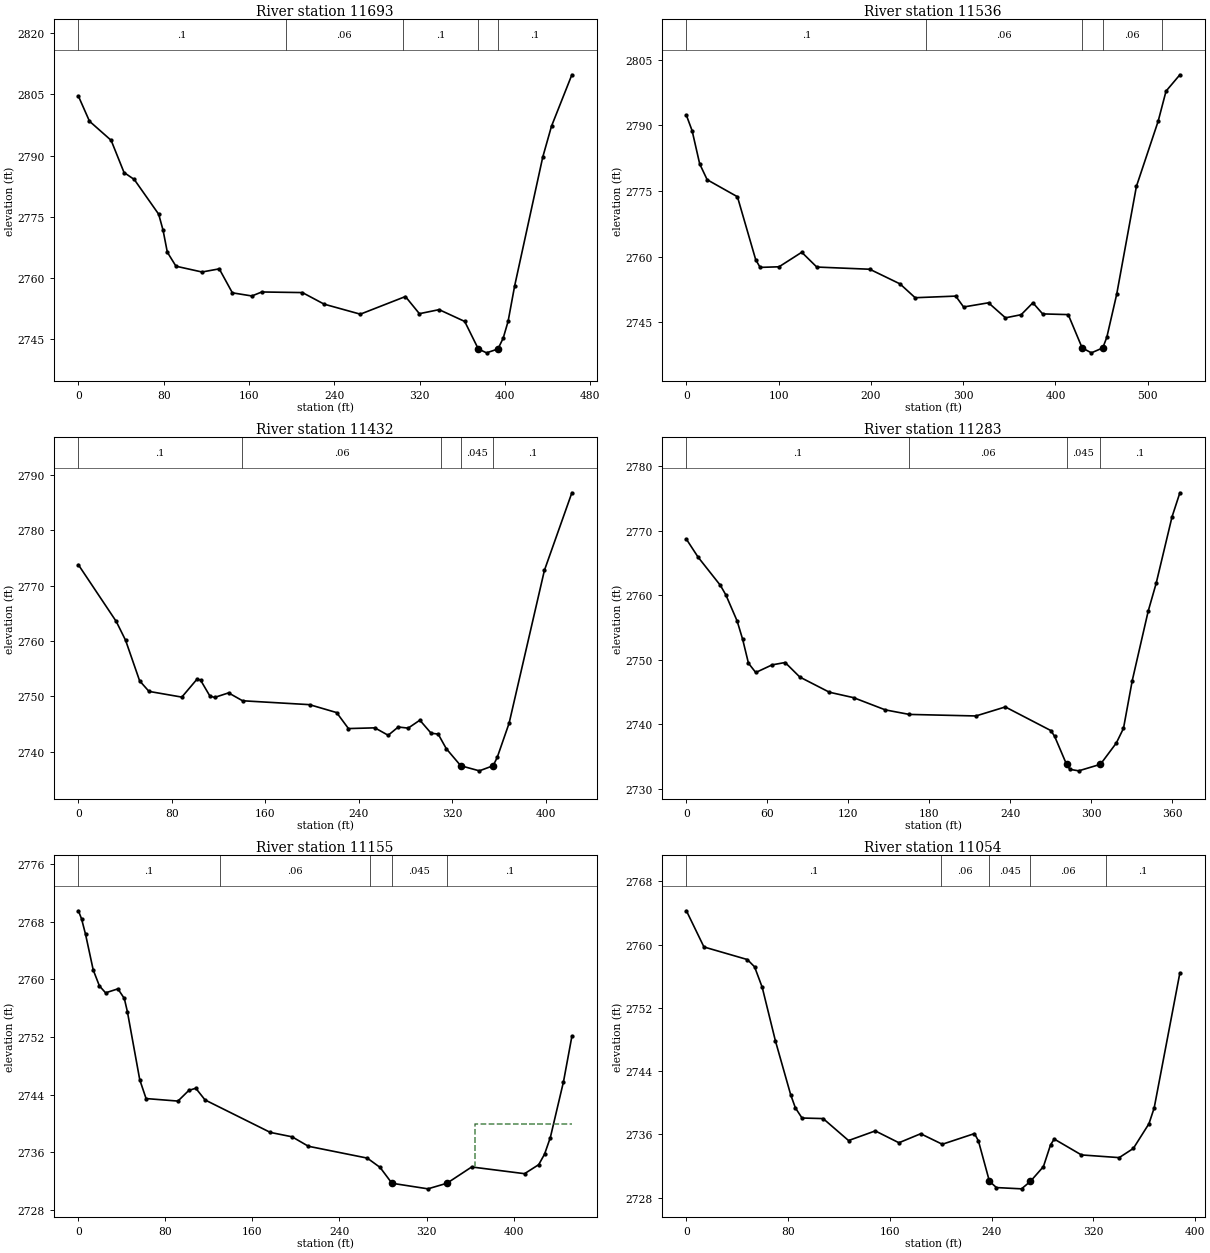
Type RM Length L Ch R = 1 ,11693   ,157.5,157.5,157.5
XS GIS Cut Line= 3
2196094.42420738588691.2897542222195952.06034014588667.321800904
2195676.42546517588826.700950616
#Sta/Elev= 30
       0 2804.59    10.4 2798.44    30.7 2793.76    42.8 2785.88    52.4 2784.17
    75.3 2775.66    79.4 2771.74    83.4 2766.36    91.5 2762.93   115.9 2761.51
   132.1 2762.28   144.4 2756.41   162.7 2755.64     172 2756.62   210.1 2756.47
   230.5 2753.63   264.4 2751.18   306.7  2755.5   319.8  2751.3   338.3 2752.29
   362.3  2749.4  375.052742.656   382.8 2741.71  393.442742.655   398.4 2745.31
     403 2749.44   409.1 2758.07   435.5 2789.67   443.7 2797.23   462.8 2809.82
#Mann= 5 ,-1,0
       0      .1       0  194.37     .06       0  304.37      .1       0
  375.05    .045       0  393.44      .1       0
Bank Sta=375.05,393.44
XS Rating Curve= 0 ,0
Exp/Cntr=0.3,0.1

Type RM Length L Ch R = 1 ,11536   ,103.6,103.6,103.6
XS GIS Cut Line= 3
2196066.19002949588608.683980185 2195787.8062518588547.171417409
2195600.90269567588712.782163345
#Sta/Elev= 30
       0 2792.31     6.2 2788.78    14.4  2781.2    22.5 2777.58    55.3 2773.69
    75.1  2759.3    79.9 2757.54   100.4 2757.68     125    2761   141.3 2757.62
   198.7 2757.12   231.5 2753.77   247.9 2750.61   291.9 2750.98   300.4 2748.49
   327.4 2749.45   345.8 2746.01   362.8 2746.73   375.5 2749.45   386.1 2746.91
   413.8 2746.75   428.9 2739.14   438.9 2738.01  451.19 2739.13   455.6 2741.55
   466.3 2751.37   487.7 2776.06   511.3 2790.98   519.8 2797.83   534.8 2801.57
#Mann= 5 ,-1,0
       0      .1       0     260     .06       0   428.9    .045       0
  451.19     .06       0   515.1      .1       0
Bank Sta=428.9,451.19
XS Rating Curve= 0 ,0
Exp/Cntr(USF)=0,0
Exp/Cntr=0.3,0.1

Type RM Length L Ch R = 1 ,11432   ,149.1,149.1,149.1
XS GIS Cut Line= 3
2195695.53740763588268.7876397152195686.86255904588469.097780038
2195549.64222669588643.383374572
#Sta/Elev= 30
       0 2773.74    32.4 2763.52    40.4 2760.12    52.4 2752.82    60.4 2750.92
    88.5 2749.89   101.5 2753.12   104.5 2752.97   112.5 2750.09   116.5 2749.83
   128.5 2750.65   140.5 2749.23   197.8 2748.53     221  2747.1   231.1 2744.22
   253.7 2744.35   265.1 2743.01   273.7  2744.5   282.2  2744.3   292.2 2745.73
   301.8 2743.39   307.9 2743.22   314.8  2740.6  327.19 2737.52   343.1  2736.6
   354.92737.518   358.4 2739.01   368.6  2745.2   398.8 2772.74   422.3 2786.72
#Mann= 5 ,-1,0
       0      .1       0     140     .06       0   310.5      .1       0
  327.19    .045       0   354.9      .1       0
Bank Sta=327.19,354.9
XS Rating Curve= 0 ,0
Exp/Cntr(USF)=0,0
Exp/Cntr=0.3,0.1

Type RM Length L Ch R = 1 ,11283   ,128.1,128.1,128.1
XS GIS Cut Line= 3
2195656.48407648588268.7266472082195645.39902204588312.693655654
2195428.26933539588548.324014546
#Sta/Elev= 30
       0  2768.7     8.7 2765.91    25.2 2761.54    29.3 2760.04    37.6 2756.02
    41.7 2753.17      46 2749.47    51.4 2748.03    63.5 2749.21    73.2 2749.58
    84.1 2747.32     106 2744.97   123.9 2744.13   147.5 2742.23   165.2 2741.53
   214.6 2741.29   236.4 2742.69   270.2 2739.02     273 2738.11  281.782733.792
   284.3 2733.01   290.8 2732.78  306.912733.792   318.7  2737.1     324 2739.37
   330.5 2746.78   342.3 2757.53   348.2 2761.84     360 2772.18   365.8  2775.9
#Mann= 4 ,-1,0
       0      .1       0  165.34     .06       0  281.78    .045       0
  306.91      .1       0
Bank Sta=281.78,306.91
XS Rating Curve= 0 ,0
Exp/Cntr=0.3,0.1

Type RM Length L Ch R = 1 ,11155   ,101.3,101.3,101.3
XS GIS Cut Line= 6
2195597.92585571588239.9281744412195467.20770732588414.617213956
2195325.01572971588422.6873325232195292.10223035588410.069019749
2195271.88601047588422.090861826   2195257.50492588452.790382591
#Sta/Elev= 30
       0 2769.49     2.9 2768.37     6.6 2766.21    13.6  2761.3    19.3 2759.08
      25 2758.12    36.3 2758.67    42.2 2757.34      45 2755.53    56.4 2746.07
    62.2 2743.47    91.5 2743.12   101.5  2744.6   107.9  2744.9   116.4 2743.28
   176.4 2738.78   196.4 2738.17   211.4 2736.86   265.5 2735.22   277.3 2733.93
   288.22731.733   321.3 2730.96   338.82731.737   361.5 2733.99   410.1 2733.06
   423.1 2734.31   428.5 2735.77   433.8 2738.07   445.9 2745.81   453.6 2752.08
#Mann= 5 ,-1,0
       0      .1       0     130     .06       0  268.18      .1       0
   288.2    .045       0   338.8      .1       0
#XS Ineff= 1 ,-1
364.3968   453.3    2740
Permanent Ineff=
       F
Bank Sta=288.2,338.8
XS Rating Curve= 0 ,0
Exp/Cntr=0.3,0.1

Type RM Length L Ch R = 1 ,11054   ,258.8,258.8,258.8
XS GIS Cut Line= 3
2195470.09818068588147.6248202192195246.20425563 588413.47902427
2195237.05395367588452.810279351
#Sta/Elev= 30
       0 2764.28    13.8  2759.7    47.9 2758.11    53.6 2757.19    59.6  2754.6
      70 2747.81      82    2741    85.7 2739.34    90.9 2738.06   107.5 2737.99
   127.5 2735.21   148.5 2736.43   167.1 2734.93   184.2 2736.07   201.2 2734.74
   226.5 2736.09   229.6 2735.17  238.262730.052   243.8 2729.26   263.5  2729.1
  270.532730.051   280.7 2731.91   286.3 2734.66   289.2  2735.4   310.6 2733.39
   340.3 2733.05   351.4 2734.21   363.7 2737.34   367.8 2739.34     388 2756.42
#Mann= 5 ,-1,0
       0      .1       0     200     .06       0  238.26    .045       0
  270.53     .06       0     330      .1       0
Bank Sta=238.26,270.53
XS Rating Curve= 0 ,0
Exp/Cntr(USF)=0,0
Exp/Cntr=0.3,0.1

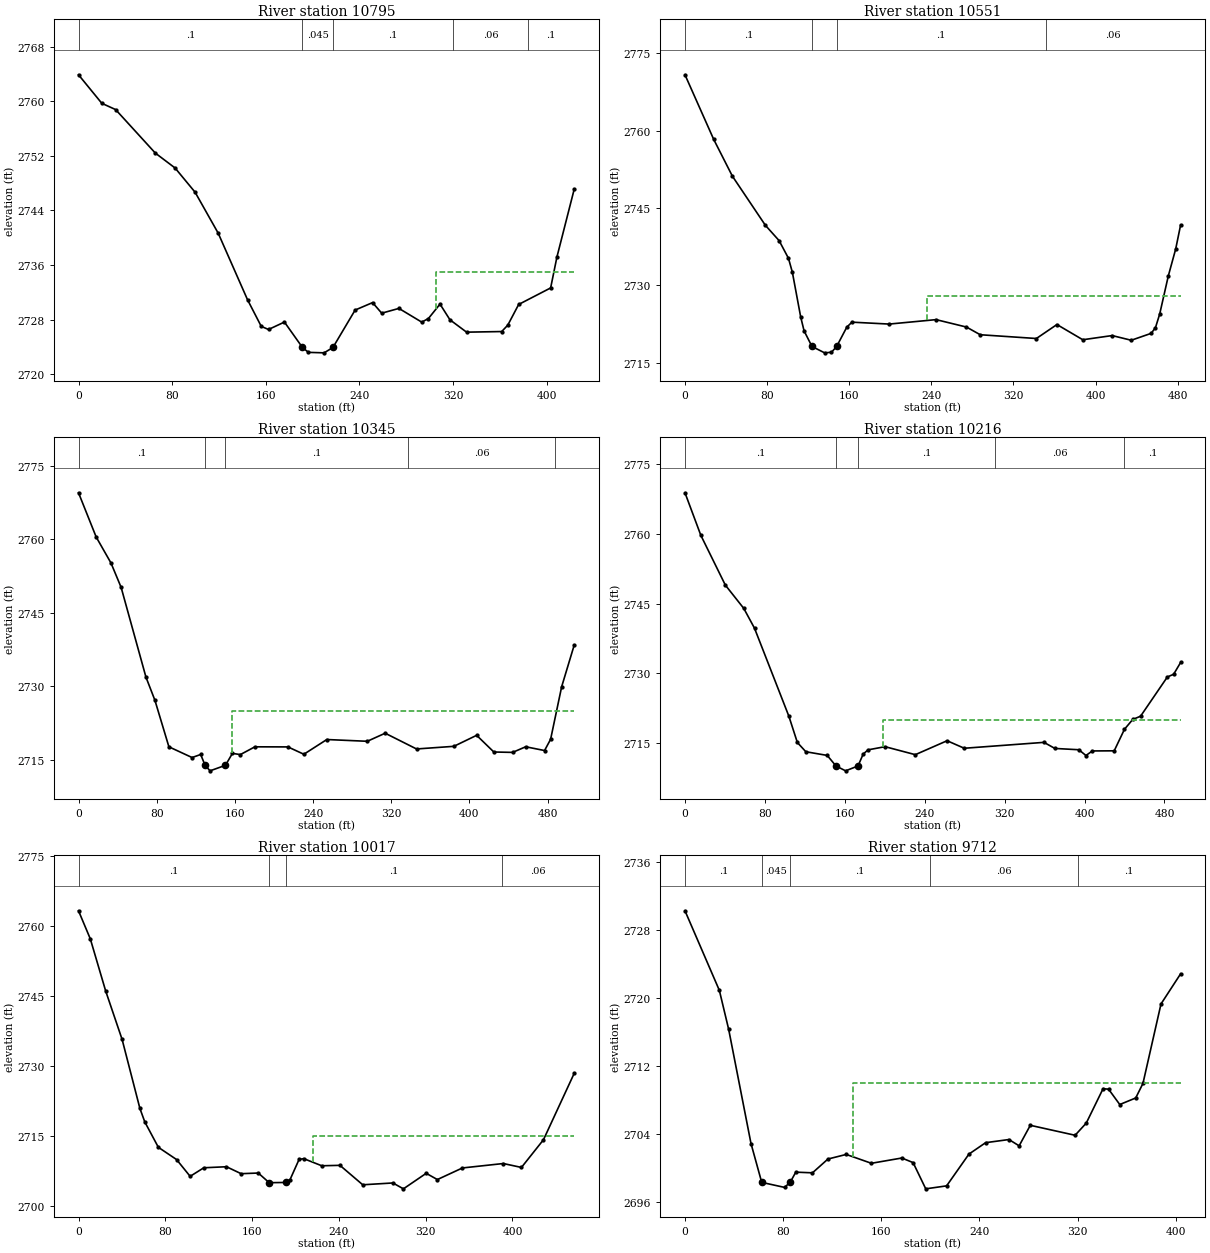
Type RM Length L Ch R = 1 ,10795   ,243.6,243.6,243.6
XS GIS Cut Line= 3
2195254.95109797588031.1901620162194995.79834504588287.031417021
2194965.20919648 588337.73741548
#Sta/Elev= 30
       0 2763.88    19.9  2759.7    31.7 2758.78    65.6 2752.41    82.5 2750.22
    99.6 2746.67   119.3 2740.68   144.4 2730.91   156.1 2727.02   162.3 2726.56
   175.9 2727.65   191.32723.926   196.4 2723.21   209.8 2723.14  217.342723.926
   236.3 2729.41   251.2  2730.5     259 2728.95   273.7 2729.65   293.2 2727.64
   298.9 2728.17   308.8 2730.28   317.3 2727.98   331.5 2726.17   361.5 2726.26
   366.7  2727.2     376 2730.23   403.3 2732.65   408.7  2737.2   423.4 2747.09
#Mann= 5 ,-1,0
       0      .1       0   191.3    .045       0  217.34      .1       0
     320     .06       0  384.16      .1       0
#XS Ineff= 2 , 0
                        305.4575            2735
Permanent Ineff=
       F       F
Bank Sta=191.3,217.34
XS Rating Curve= 0 ,0
Exp/Cntr=0.3,0.1

Type RM Length L Ch R = 1 ,10551   ,206.6,206.6,206.6
XS GIS Cut Line= 4
2195045.40547813587868.5310493692194997.12083167587957.868543157
2194715.58634048588168.0608765422194706.74668328588196.647605501
#Sta/Elev= 30
       0 2770.86      28 2758.32    46.2 2751.19    78.3 2741.67    91.7 2738.69
   100.8 2735.27   104.6 2732.56   112.7  2723.9     116  2721.2  123.682718.169
     136 2716.93   142.7 2717.04  147.742718.166   157.6  2721.9   162.6 2722.88
   198.9 2722.51   244.6 2723.37   274.2 2721.93   287.6 2720.44   342.3 2719.71
   362.3 2722.42   387.5 2719.47   416.1 2720.28   434.7 2719.37   454.1 2720.71
   458.3 2721.82   462.4 2724.45   470.8 2731.85     478 2737.08   482.8 2741.75
#Mann= 4 ,-1,0
       0      .1       0  123.68    .045       0  147.74      .1       0
  351.55     .06       0
#XS Ineff= 2 , 0
                        235.8285            2728
Permanent Ineff=
       F       F
Bank Sta=123.68,147.74
XS Rating Curve= 0 ,0
Exp/Cntr=0.3,0.1

Type RM Length L Ch R = 1 ,10345   ,129,129,129
XS GIS Cut Line= 4
2194937.46130682 587748.669788012194856.58975246587791.834246826
2194745.47078569587988.1470004462194616.23413974588127.411658147
#Sta/Elev= 30
       0 2769.54    18.1 2760.49    33.2  2755.2    43.6 2750.21      69 2731.87
    78.2 2727.12    92.5 2717.62   116.2 2715.43     125 2716.05  129.522713.844
   134.6 2712.71  150.362713.844   157.5 2716.28   165.6 2716.03   180.5 2717.62
   214.3  2717.6   230.6  2716.1   254.1 2719.11   295.5 2718.75   313.8  2720.4
   345.9 2717.18   384.1 2717.72   407.4 2719.97     425 2716.56   444.2 2716.48
   457.6 2717.63   476.9 2716.86   483.1 2719.16   494.4  2729.9   507.2 2738.38
#Mann= 5 ,-1,0
       0      .1       0  129.52    .045       0  150.36      .1       0
  337.25     .06       0  487.25      .1       0
#XS Ineff= 2 , 0
                          157.53            2725
Permanent Ineff=
       F       F
Bank Sta=129.52,150.36
XS Rating Curve= 0 ,0
Exp/Cntr=0.3,0.1

Type RM Length L Ch R = 1 ,10216   ,198.4,198.4,198.4
XS GIS Cut Line= 2
2194860.03474796587638.2315133992194490.26655893587969.112641955
#Sta/Elev= 30
       0 2768.89    15.9 2759.72    40.4 2749.02    58.9 2743.99    69.6 2739.74
     104  2720.8   112.5 2715.14     121 2713.15   142.4 2712.36  151.152710.093
   160.8 2709.04  173.242710.093   178.4 2712.65   183.3 2713.56   200.3 2714.24
   230.6 2712.52   262.4 2715.52   279.6  2713.9   359.4 2715.17   370.3 2713.86
   394.3 2713.58   401.4 2712.34   407.8 2713.32   429.7 2713.35     440    2718
   448.3 2720.11   456.1  2720.8   482.9 2729.24   489.2 2729.83496.1964 2732.37
#Mann= 5 ,-1,0
       0      .1       0  151.15    .045       0  173.24      .1       0
     310     .06       0     440      .1       0
#XS Ineff= 2 , 0
                           198.4            2720
Permanent Ineff=
       F       F
Bank Sta=151.15,173.24
XS Rating Curve= 0 ,0
Exp/Cntr(USF)=0,0
Exp/Cntr=0.3,0.1

Type RM Length L Ch R = 1 ,10017   ,305.2,305.2,305.2
XS GIS Cut Line= 2
 2194802.5870445587532.3253250612194365.71957251587666.087471854
#Sta/Elev= 30
       0 2763.32    10.9 2757.28      25 2746.14    40.2 2735.71    56.6 2720.91
    61.1 2718.03    73.6 2712.58    90.4 2709.95   102.9 2706.35   115.5 2708.19
   136.4 2708.41   149.9 2706.92   165.7 2707.06  175.792704.989   191.6 2705.04
     195 2705.65   203.3 2709.97   207.6 2710.15   224.2 2708.62     241 2708.71
     262 2704.54   289.8 2704.93   299.5 2703.67   320.5    2707   330.8 2705.66
   353.9 2708.15   391.6  2709.1   408.3 2708.26   428.6  2714.2   456.9 2728.43
#Mann= 4 ,-1,0
       0      .1       0  175.79    .045       0   191.6      .1       0
     390     .06       0
#XS Ineff= 2 , 0
                        215.7843            2715
Permanent Ineff=
       F       F
Bank Sta=175.79,191.6
XS Rating Curve= 0 ,0
Exp/Cntr=0.3,0.1

Type RM Length L Ch R = 1 ,9712    ,294.1,294.1,294.1
XS GIS Cut Line= 2
2194611.48319686587266.4497728112194256.58760289587459.247725243
#Sta/Elev= 30
       0 2730.23      28 2720.89    35.6 2716.31    53.8  2702.9   62.53 2698.34
    81.1 2697.75    85.7 2698.34    90.3 2699.54   103.9 2699.46   116.5 2701.08
   131.4 2701.62   151.9 2700.58   176.7  2701.2   185.9 2700.66   196.2 2697.58
   213.2 2697.93   231.4 2701.66     245    2703     264 2703.37   272.3 2702.63
   281.4 2705.04   317.9 2703.87     327  2705.3   340.7 2709.34   345.2 2709.28
   354.3 2707.48   367.3 2708.25   373.2 2709.96   387.9 2719.29   403.9 2722.83
#Mann= 5 ,-1,0
       0      .1       0   62.53    .045       0    85.7      .1       0
     200     .06       0     320      .1       0
#XS Ineff= 2 , 0
                        136.7763            2710
Permanent Ineff=
       F       F
Bank Sta=62.53,85.7
XS Rating Curve= 0 ,0
Exp/Cntr(USF)=0,0
Exp/Cntr=0.3,0.1

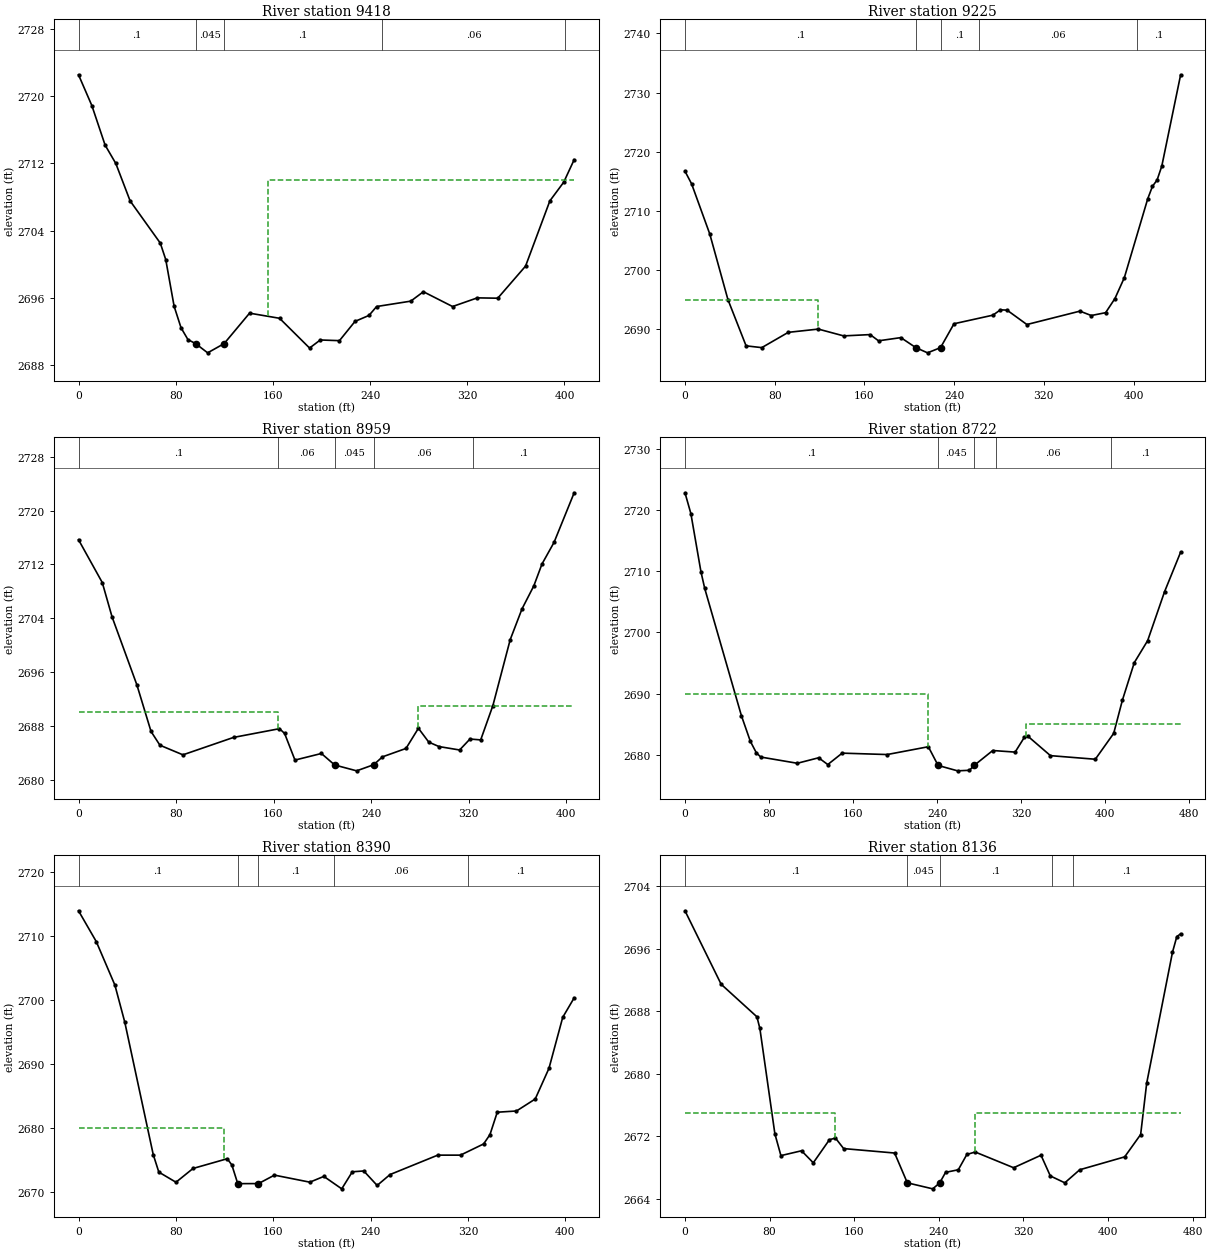
Type RM Length L Ch R = 1 ,9418    ,193.4,193.4,193.4
XS GIS Cut Line= 4
 2194529.3717107586997.0098460032194461.81305549587014.399277563
2194241.98085823587173.0101392472194201.88189136 587226.94196482
#Sta/Elev= 30
       0 2722.53      11 2718.86    21.9 2714.16    30.7 2711.98    42.5 2707.52
    67.3 2702.51    71.8 2700.55    78.7 2694.99    84.4 2692.43    90.1 2691.02
    96.4 2690.55   106.3 2689.45  119.88 2690.55   140.8 2694.17   165.5 2693.56
   190.2 2690.02     199 2690.98   214.8  2690.9   227.6 2693.19   239.1  2693.9
   245.4 2694.96   273.5  2695.6   283.9 2696.72   307.9 2694.96   328.3 2695.99
   345.1 2695.95     368 2699.77     388 2707.53   399.4 2709.75     408 2712.43
#Mann= 5 ,-1,0
       0      .1       0    96.4    .045       0  119.88      .1       0
  249.76     .06       0  400.84      .1       0
#XS Ineff= 2 , 0
                        155.6667            2710
Permanent Ineff=
       F       F
Bank Sta=96.4,119.88
XS Rating Curve= 0 ,0
Exp/Cntr=0.3,0.1

Type RM Length L Ch R = 1 ,9225    ,265.9,265.9,265.9
XS GIS Cut Line= 4
2194438.05590082586812.2959700242194376.19601139586821.673331334
2194165.98118503587050.3282574242194100.08440139 587070.36479412
#Sta/Elev= 30
       0 2716.72     5.9 2714.59    22.1 2706.13    38.3 2695.05    54.5 2687.24
    68.5 2686.94    92.1 2689.52   118.9 2690.07   141.5 2688.92   165.1 2689.14
   172.6 2688.09   192.5 2688.63  205.87 2686.94   216.3 2686.06  227.89 2686.94
   239.9 2690.97   274.6 2692.42   281.3 2693.32   287.2 2693.27   304.9 2690.84
   352.2  2693.1   362.3 2692.36   375.1 2692.84   383.4 2695.22   391.8 2698.75
   412.7 2712.09   416.9 2714.18     421 2715.23   425.2 2717.58     442    2733
#Mann= 5 ,-1,0
       0      .1       0  205.87    .045       0  227.89      .1       0
  262.57     .06       0  403.17      .1       0
#XS Ineff= 2 , 0
        119.0651    2695
Permanent Ineff=
       F       F
Bank Sta=205.87,227.89
XS Rating Curve= 0 ,0
Exp/Cntr=0.3,0.1

Type RM Length L Ch R = 1 ,8959    ,236.4,236.4,236.4
XS GIS Cut Line= 4
  2194395.711623586643.8008838772194331.91592492586645.145162495
2194083.03600666586729.454215801 2194016.7841966586774.428672647
#Sta/Elev= 30
       0 2715.67    19.5  2709.3    27.5 2704.21    47.9 2694.08    59.5 2687.16
    66.8 2685.11    85.7 2683.68   127.2 2686.27   164.9 2687.57   169.1 2686.86
   177.6  2682.9   199.3 2683.88   210.2 2682.17   228.2  2681.3   242.2 2682.21
   249.4 2683.38   268.7 2684.63   278.9 2687.63   287.4 2685.57   295.8 2684.91
   312.7  2684.4   321.2 2686.03     330  2685.9     340    2691   354.2  2700.8
   363.9 2705.38   373.6 2708.81   380.3 2712.06   390.2 2715.28   406.7 2722.65
#Mann= 5 ,-1,0
       0      .1       0  163.81     .06       0   210.2    .045       0
   242.2     .06       0  323.81      .1       0
#XS Ineff= 2 , 0
        163.3631    2690   278.9            2691
Permanent Ineff=
       F       F
Bank Sta=210.2,242.2
XS Rating Curve= 0 ,0
Exp/Cntr=0.3,0.1

Type RM Length L Ch R = 1 ,8722    ,332.5,332.5,332.5
XS GIS Cut Line= 4
2194299.41105832586364.4896028852194243.51127615586415.646828152
2193949.77839522586540.7244674952193892.80361249586592.089406372
#Sta/Elev= 30
       0 2722.89     5.6 2719.49    15.2 2709.95    18.8 2707.21    53.7 2686.37
    62.2 2682.17    67.9 2680.29    72.1 2679.59   106.9 2678.57   127.2 2679.47
   135.9 2678.36   149.6 2680.23   192.4    2680   231.6 2681.28  240.892678.214
   259.4 2677.33   270.7 2677.42   275.22678.215   292.9 2680.66   314.2  2680.4
   322.9  2682.8   326.5 2682.98   347.8 2679.82   390.5 2679.23     408 2683.47
   416.3 2688.92   427.6 2695.06   440.3 2698.66   456.4 2706.68   471.7 2713.16
#Mann= 5 ,-1,0
       0      .1       0  240.89    .045       0   275.2      .1       0
  295.77     .06       0  405.03      .1       0
#XS Ineff= 2 , 0
          231.57    2690  324.72            2685
Permanent Ineff=
       F       F
Bank Sta=240.89,275.2
XS Rating Curve= 0 ,0
Exp/Cntr=0.3,0.1

Type RM Length L Ch R = 1 ,8390    ,254.2,254.2,254.2
XS GIS Cut Line= 3
2194120.67766688586092.6013210452193836.82542594586264.427822644
 2193781.2974414586315.558270632
#Sta/Elev= 30
       0 2713.89    14.6 2709.08    29.9 2702.29      38 2696.52    61.4 2675.84
      66  2673.1    80.1 2671.52    94.1 2673.67   122.2 2675.19     126 2674.22
  130.86  2671.3   147.9 2671.31     161 2672.63   190.1 2671.53   201.6 2672.43
   216.3 2670.49     225 2673.15   234.4 2673.28   245.4 2671.02     256 2672.72
   295.2 2675.75   313.9 2675.75   332.9  2677.5   338.1 2678.95   344.1 2682.45
   359.9 2682.64   375.3 2684.51   386.6  2689.3   397.9 2697.26   407.3  2700.3
#Mann= 5 ,-1,0
       0      .1       0  130.86    .045       0   147.9      .1       0
     210     .06       0     320      .1       0
#XS Ineff= 2 , 0
        119.9316    2680
Permanent Ineff=
       F       F
Bank Sta=130.86,147.9
XS Rating Curve= 0 ,0
Exp/Cntr=0.3,0.1

Type RM Length L Ch R = 1 ,8136    ,280.5,280.5,280.5
XS GIS Cut Line= 4
2194054.94066423585944.4197515792193943.39109109586033.474681981
2193750.37640709586015.5506805522193657.66940681586109.524461142
#Sta/Elev= 30
       0 2700.86    34.2 2691.46      68  2687.3    70.8 2685.81      85 2672.32
    90.7 2669.54   110.2 2670.16   121.3 2668.62   136.6 2671.58   142.3 2671.78
     150 2670.44   198.2 2669.87   210.2 2666.06   234.2 2665.29  240.77 2666.04
   246.4  2667.4   258.4 2667.73   266.5 2669.69   274.4    2670   310.7 2667.99
   336.6 2669.59   345.4 2666.94   359.1 2666.06   373.2 2667.73   415.7 2669.38
   430.8 2672.24   436.5  2678.8   460.9 2695.56     465 2697.56   468.6 2697.91
#Mann= 5 ,-1,0
       0      .1       0   210.2    .045       0  240.77      .1       0
  346.58     .06       0  366.58      .1       0
#XS Ineff= 2 , 0
           141.7    2675274.2838            2675
Permanent Ineff=
       F       F
Bank Sta=210.2,240.77
XS Rating Curve= 0 ,0
Exp/Cntr=0.3,0.1

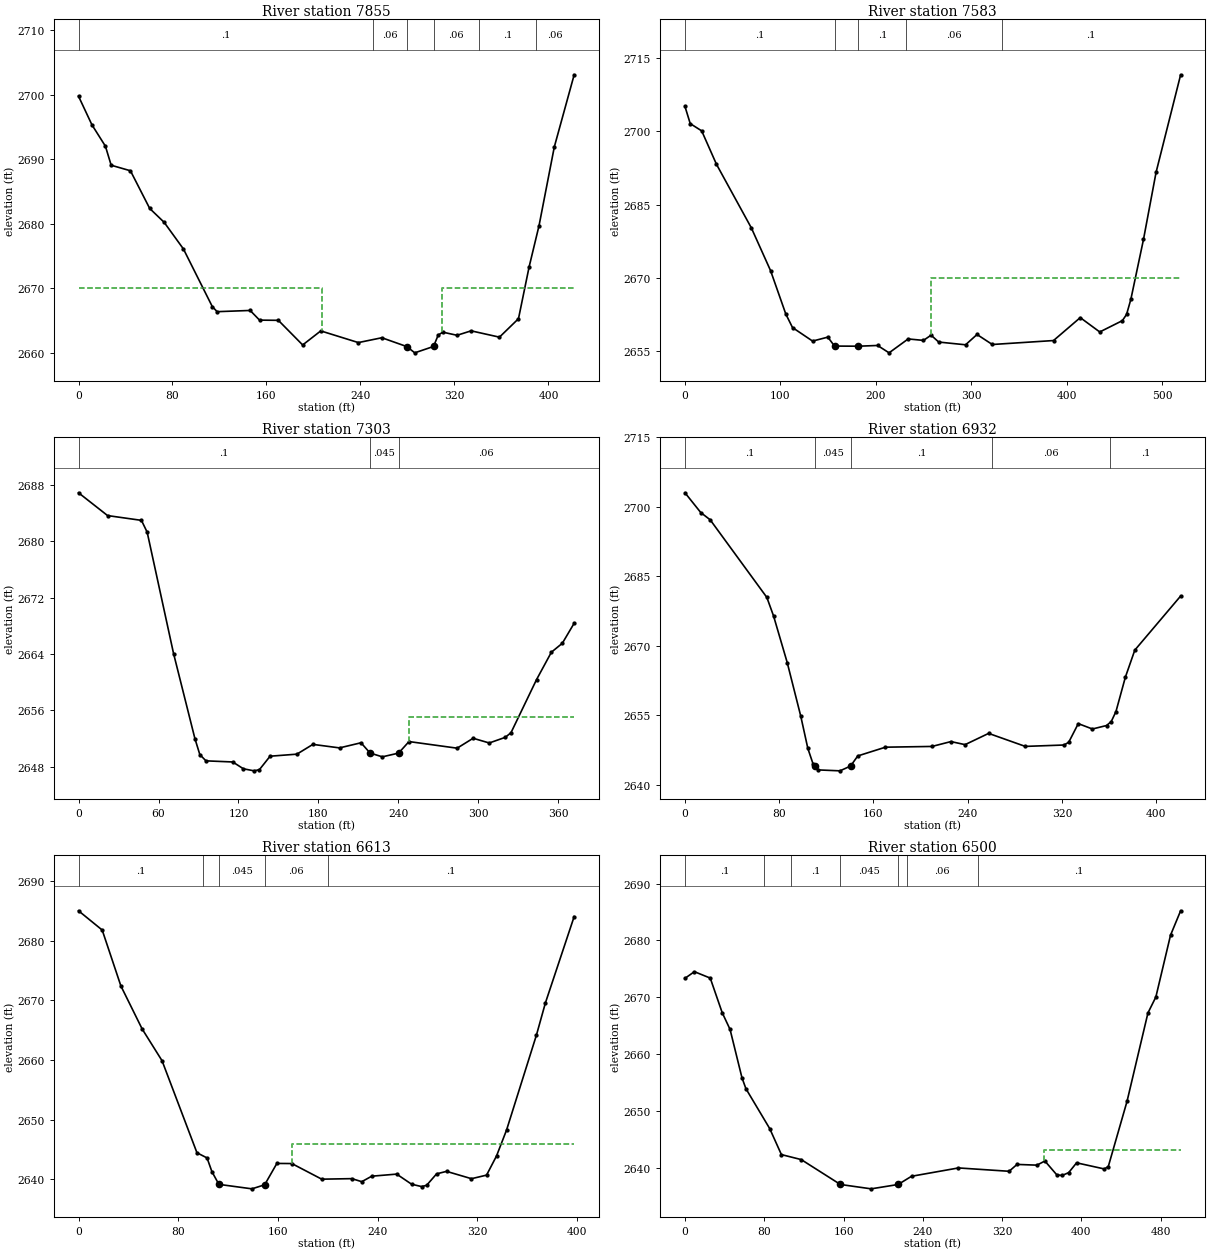
Type RM Length L Ch R = 1 ,7855    ,271.9,271.9,271.9
XS GIS Cut Line= 4
2193987.34194195585799.3493566712193869.44384571585825.706937668
2193620.61430955585835.5413066292193572.62549816585855.742218292
#Sta/Elev= 30
       0 2699.77    11.4 2695.34    22.9 2692.02    27.8 2689.07    44.2 2688.21
    60.6 2682.37    72.9 2680.22    89.3 2676.09   113.9 2667.15     118 2666.37
   146.1 2666.56   154.1 2665.06   170.1 2665.03   190.8 2661.21   206.2 2663.39
   238.2 2661.58   258.2 2662.33  279.61 2660.95   286.2 2659.99   302.2 2660.98
   306.2 2662.76   310.2 2663.19   322.2 2662.71   334.2  2663.4   358.3 2662.42
   374.5 2665.28   383.6 2673.35     392 2679.71     405 2691.91421.8995 2703.09
#Mann= 6 ,-1,0
       0      .1       0  250.81     .06       0  279.61    .045       0
   302.2     .06       0  340.81      .1       0  389.83     .06       0
#XS Ineff= 2 , 0
         207.075    2670 309.769            2670
Permanent Ineff=
       F       F
Bank Sta=279.61,302.2
XS Rating Curve= 0 ,0
Exp/Cntr=0.3,0.1

Type RM Length L Ch R = 1 ,7583    ,280.6,280.6,280.6
XS GIS Cut Line= 4
2193973.67910942 585597.74999532  2193862.045496585594.124781452
2193516.86659382585610.673771546 2193460.9167404 585636.75717742
#Sta/Elev= 30
       0 2705.12     5.5 2701.61    17.5 2700.12      33 2693.26    69.5 2680.23
    89.6 2671.48   105.6 2662.56   112.6  2659.8   133.6 2657.03   149.6 2657.84
  156.572656.008   181.6 2655.98   201.7 2656.13   213.7 2654.62   233.7 2657.47
   249.7 2657.17   257.7 2658.24   265.7 2656.83   293.8 2656.27   305.8 2658.38
   321.8 2656.33   385.9 2657.14   413.9 2661.84   434.3  2658.9     458 2661.22
   462.4  2662.5   466.9 2665.61   480.1 2677.86   493.3 2691.64     519 2711.62
#Mann= 5 ,-1,0
       0      .1       0  156.57    .045       0   181.6      .1       0
  231.69     .06       0  331.69      .1       0
#XS Ineff= 1 ,-1
 257.427 518.999    2670
Permanent Ineff=
       F
Bank Sta=156.57,181.6
XS Rating Curve= 0 ,0
Exp/Cntr=0.3,0.1

Type RM Length L Ch R = 1 ,7303    ,370.8,370.8,370.8
XS GIS Cut Line= 4
2193945.85379218585377.4421238922193869.69229179585322.194185565
2193639.96255439585337.2199399642193602.81014734585307.655489009
#Sta/Elev= 30
       0 2686.91    21.8 2683.67    47.2 2682.99    51.5 2681.31    71.3 2664.06
    87.3 2651.98      91  2649.7    95.6 2648.81   115.7 2648.65   123.7 2647.68
   131.7 2647.39   135.7 2647.56   143.7 2649.47   163.8 2649.76   175.8 2651.15
   195.8 2650.65   211.9 2651.38   218.7 2649.92   227.9 2649.38  240.08 2649.91
   247.9 2651.55     284 2650.61     296 2652.02   308.1 2651.35   320.1 2652.15
   324.4 2652.81   343.6 2660.37   354.7 2664.25   362.9 2665.52371.7906 2668.37
#Mann= 3 ,-1,0
       0      .1       0   218.7    .045       0  240.08     .06       0
#XS Ineff= 2 , 0
                          247.94            2655
Permanent Ineff=
       F       F
Bank Sta=218.7,240.08
XS Rating Curve= 0 ,0
Exp/Cntr=0.3,0.1

Type RM Length L Ch R = 1 ,6932    ,318.8,318.8,318.8
XS GIS Cut Line= 4
2193993.60655972585129.1102335912193921.60293566585131.902610462
2193795.03635489585188.9990228032193585.29844334585181.107263612
#Sta/Elev= 30
       0 2703.03    13.4 2698.76    21.4 2697.19    69.5 2680.43    75.2 2676.42
    86.8 2666.35    98.3 2654.77   104.3 2647.81   108.7 2644.49   110.4 2643.96
   113.1 2643.16   131.6 2642.96   140.6    2644   146.7 2646.18   170.2 2648.07
   209.7 2648.23   225.8 2649.28   237.8 2648.62   257.8 2651.05   288.9 2648.24
   321.8 2648.54   325.8 2649.14   333.9 2653.16   345.9    2652   357.9 2652.75
   361.9 2653.61   365.9 2655.77   373.9 2663.21   381.9 2669.04   420.8 2680.72
#Mann= 5 ,-1,0
       0      .1       0   110.4    .045       0   140.6      .1       0
  260.91     .06       0  360.91      .1       0
Bank Sta=110.4,140.6
XS Rating Curve= 0 ,0
Exp/Cntr=0.3,0.1

Type RM Length L Ch R = 1 ,6613    ,113.6,113.6,113.6
XS GIS Cut Line= 2
2193943.13743874584836.7152381022193545.92847799584853.391950195
#Sta/Elev= 30
       0 2685.03      19  2681.8      34 2672.42      51 2665.23      67 2659.89
      95 2644.46   103.1 2643.59     107 2641.29  112.59 2639.16   139.1 2638.41
  149.31 2639.09   159.1 2642.67   171.1 2642.65   195.1 2640.03   219.2 2640.12
   227.2 2639.61   235.2 2640.53   255.2 2640.88   267.2 2639.18   275.2 2638.79
   279.2    2639   287.2 2640.92   295.2 2641.34   315.2 2640.11   327.3 2640.71
   335.3 2643.93   343.3 2648.25   367.3 2664.19   374.5 2669.59397.5589 2684.06
#Mann= 5 ,-1,0
       0      .1       0     100     .06       0  112.59    .045       0
  149.31     .06       0     200      .1       0
#XS Ineff= 2 , 0
                          171.11            2646
Permanent Ineff=
       F       F
Bank Sta=112.59,149.31
XS Rating Curve= 0 ,0
Exp/Cntr(USF)=0,0
Exp/Cntr=0.3,0.1

Type RM Length L Ch R = 1 ,6500    ,88.3,88.3,88.3
XS GIS Cut Line= 6
2193921.69065411584649.6245342922193824.45224724584652.131049199
2193803.80288403584715.2508135372193762.62581714584777.952256309
 2193747.8451218584832.7458305522193543.23040392 584840.34376999
#Sta/Elev= 30
       0 2673.31     9.5 2674.48    25.5 2673.35    37.5 2667.29    45.5 2664.31
    57.5 2655.81    61.5 2653.88    85.5 2646.86    97.3 2642.28   117.3  2641.4
  156.872637.016   187.9 2636.25  215.082637.015   228.6 2638.46     276 2639.93
   327.1 2639.34   335.1 2640.55   355.2 2640.42   363.2 2641.15   375.2 2638.72
   380.5  2638.6   387.2  2639.1   395.2 2640.83   423.2 2639.75   427.2 2640.18
   446.1 2651.65   467.2 2667.21   475.2 2670.02     490  2680.9   500.2  2685.2
#Mann= 7 ,-1,0
       0      .1       0      80     .06       0  107.27      .1       0
  156.87    .045       0  215.08      .1       0  223.68     .06       0
  295.45      .1       0
#XS Ineff= 2 , 0
                        362.3636            2643
Permanent Ineff=
       F       F
Bank Sta=156.87,215.08
XS Rating Curve= 0 ,0
Exp/Cntr=0.3,0.1

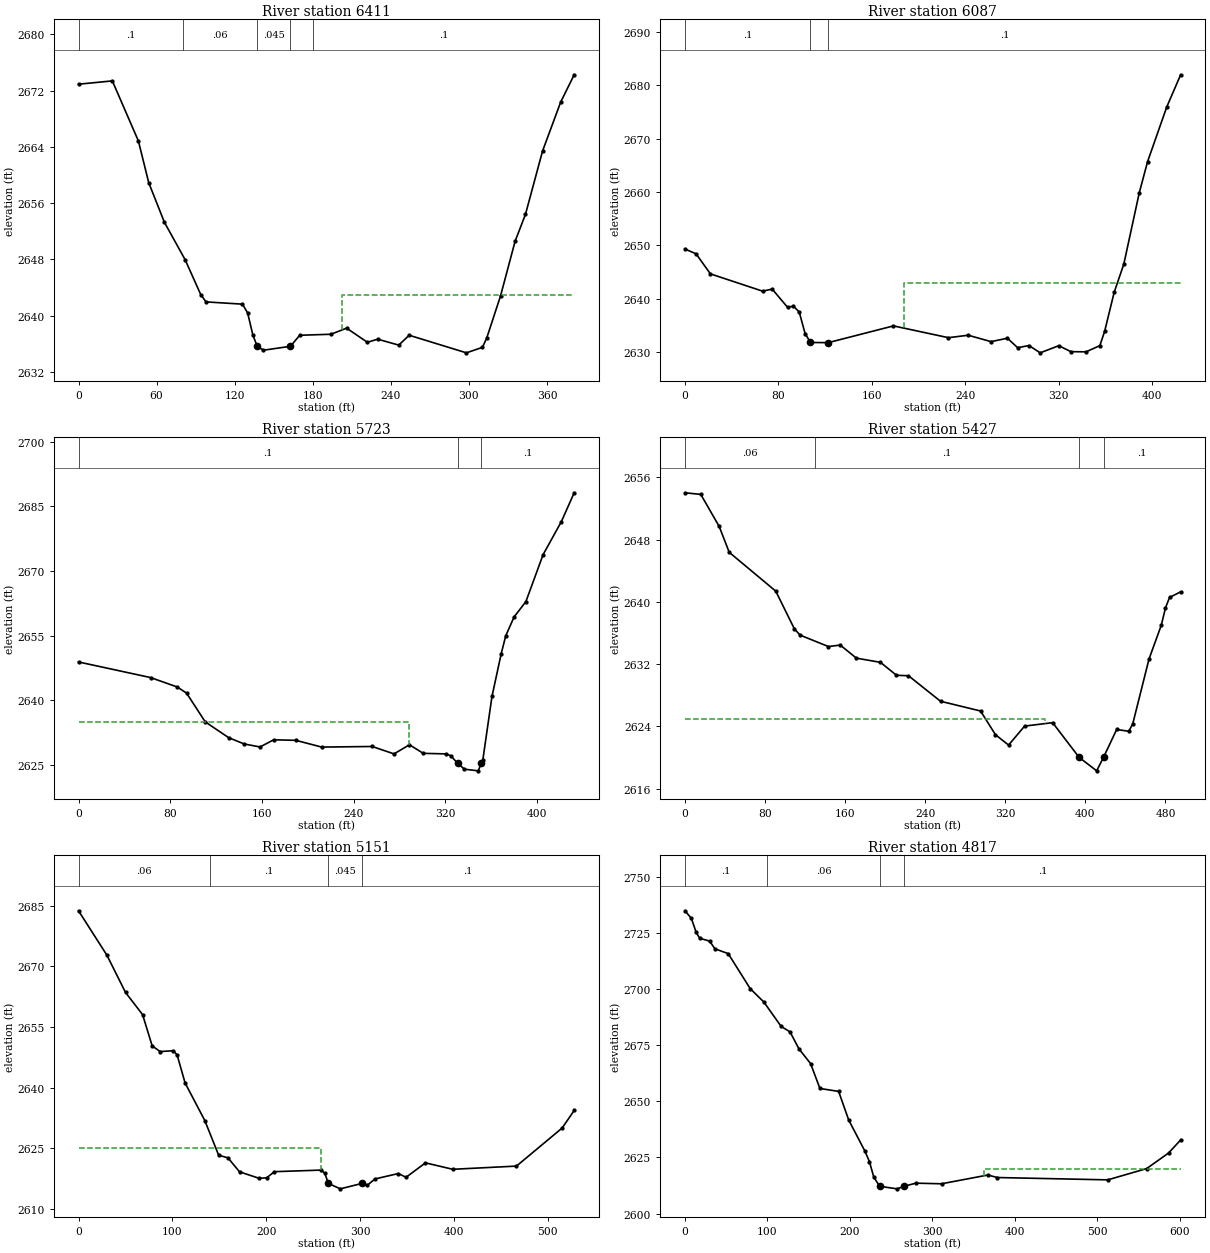
Type RM Length L Ch R = 1 ,6411    ,324.7,324.7,324.7
XS GIS Cut Line= 3
2193922.14342333584643.373494276 2193614.2894999584651.394605404
 2193551.1881747584687.930776176
#Sta/Elev= 30
       0  2672.9      26 2673.37      46 2664.84      54 2658.88      66 2653.28
      82 2647.93      94 2642.97      98 2641.96     126 2641.64     130 2640.38
     134 2637.24  137.262635.684     142 2635.09   162.9 2635.65     170 2637.22
     194 2637.36     206 2638.23     222 2636.22   229.9 2636.66   246.1 2635.82
   254.1 2637.22   298.1 2634.72   310.4  2635.5   313.7 2636.82   324.3  2642.8
   335.5 2650.57   343.5 2654.42   356.6  2663.4   370.5 2670.34   380.9 2674.24
#Mann= 5 ,-1,0
       0      .1       0      80     .06       0  137.26    .045       0
   162.9     .06       0     180      .1       0
#XS Ineff= 2 , 0
                        202.4975            2643
Permanent Ineff=
       F       F
Bank Sta=137.26,162.9
XS Rating Curve= 0 ,0
Exp/Cntr=0.3,0.1

Type RM Length L Ch R = 1 ,6087    ,363.9,363.9,363.9
XS GIS Cut Line= 5
2193773.57578268584219.7969160622193758.34817292584300.474037377
2193691.66732368584390.8964890092193585.32658704584498.921131187
2193508.58726265584515.618723194
#Sta/Elev= 30
       0  2649.3     9.5  2648.4    21.8 2644.64    66.5  2641.4    74.7 2641.79
    87.9 2638.37    92.9  2638.6    97.9 2637.48   102.9 2633.45  107.52 2631.78
   122.7 2631.75   178.6 2634.89   225.7 2632.68   242.6 2633.14   262.2 2631.94
   276.2 2632.58     285  2630.8   294.7 2631.21   304.3 2629.84   320.2 2631.18
   330.6 2630.06   343.6 2630.03   355.4 2631.19   359.5 2633.87   367.7 2641.21
   375.9 2646.45   389.2 2659.87   396.3 2665.69   412.7 2675.92   424.6 2681.96
#Mann= 3 ,-1,0
       0      .1       0  107.52    .045       0   122.7      .1       0
#XS Ineff= 2 , 0
                        187.9819            2643
Permanent Ineff=
       F       F
Bank Sta=107.52,122.7
XS Rating Curve= 0 ,0
Exp/Cntr=0.3,0.1

Type RM Length L Ch R = 1 ,5723    ,295.7,295.7,295.7
XS GIS Cut Line= 5
2193773.10478874584169.354618415 2193645.8690558584191.390619348
 2193504.7036347 584264.783075692193419.58459576584263.612044225
2193365.98136863584288.623741997
#Sta/Elev= 30
       0 2648.88    62.9 2645.26    86.2 2643.07    94.3 2641.65   110.6 2634.98
     131 2631.32   144.6 2629.85   158.4 2629.16   170.3 2630.82   189.6  2630.7
   212.2 2629.13   256.3 2629.27   275.3 2627.55   288.8 2629.67   300.8 2627.68
   320.8 2627.55   324.8 2627.12     3312625.324   336.8    2624   348.8 2623.62
  351.422625.326   352.8 2626.13   360.8 2640.88   368.8 2650.75   372.8 2654.94
   380.1 2659.33   390.4 2662.89   405.4 2673.78   421.3 2681.42432.5125 2688.13
#Mann= 3 ,-1,0
       0      .1       0     331    .045       0  351.42      .1       0
#XS Ineff= 2 , 0
        288.6885    2635
Permanent Ineff=
       F       F
Bank Sta=331,351.42
XS Rating Curve= 0 ,0
Exp/Cntr=0.3,0.1

Type RM Length L Ch R = 1 ,5427    ,275.8,275.8,275.8
XS GIS Cut Line= 4
2193743.72446237583874.3689243522193616.12053993583988.693455056
2193335.84877553583991.8049602452193293.34419713584001.354248888
#Sta/Elev= 30
       0 2654.01    15.8  2653.8    34.2 2649.68    44.2 2646.36    90.7 2641.37
   109.3 2636.52     115 2635.72   143.3 2634.25   155.1 2634.44   171.3 2632.76
   195.3 2632.22   211.3 2630.56   223.3  2630.5   255.3 2627.22   295.3 2625.97
   310.2 2622.92   323.3 2621.59   339.3 2624.03   367.3 2624.47  393.752620.015
   411.3 2618.28  418.152620.016   431.3  2623.6   443.3 2623.36   447.3  2624.3
   463.6 2632.65   475.9 2637.01     480  2639.2   484.1 2640.56495.1799 2641.28
#Mann= 4 ,-1,0
       0     .06       0     130      .1       0  393.75    .045       0
  418.15      .1       0
#XS Ineff= 2 , 0
        359.8427    2625
Permanent Ineff=
       F       F
Bank Sta=393.75,418.15
XS Rating Curve= 0 ,0
Exp/Cntr=0.3,0.1

Type RM Length L Ch R = 1 ,5151    ,334.3,334.3,334.3
XS GIS Cut Line= 4
2193618.51681348 583588.837314142193502.02662601583688.378775872
2193206.79196486583763.5612105062193154.71530154583810.912101407
#Sta/Elev= 30
       0 2683.71    30.3 2672.72    50.1 2663.53    68.3 2658.05    78.5 2650.33
      87 2648.92   101.2 2649.13   105.2 2648.01   113.6 2641.16   134.6 2631.88
   149.4  2623.3   159.3 2622.66   171.6 2619.21   192.3 2617.62   200.5 2617.72
   208.8 2619.24   258.3 2619.63   262.5 2618.86   266.3 2616.35     279    2615
   302.4 2616.35   307.9 2615.91   316.1 2617.45   340.9 2618.78   349.1 2617.85
   369.8 2621.42   398.9 2619.83   466.8 2620.62   515.5 2630.03   528.3 2634.36
#Mann= 4 ,-1,0
       0     .06       0     140      .1       0   266.3    .045       0
   302.4      .1       0
#XS Ineff= 2 , 0
           258.3    2625
Permanent Ineff=
       F       F
Bank Sta=266.3,302.4
XS Rating Curve= 0 ,0
Exp/Cntr=0.3,0.1

Type RM Length L Ch R = 1 ,4817    ,249.5,249.5,249.5
XS GIS Cut Line= 3
2193420.01212593583230.0142801662193068.12907572583626.120479745
2193038.14134777583690.586405798
#Sta/Elev= 30
       0 2734.88     7.8 2731.47    13.5 2725.32    17.8 2722.64    29.9 2721.38
    36.3 2717.93    52.4 2715.81    79.1 2700.19    95.6 2694.25   116.6 2683.37
   127.3 2680.96   138.1 2673.43   152.3 2666.79   163.6 2655.74   186.3 2654.42
   198.5 2641.67   218.2 2627.78   223.6 2623.17   228.8  2616.4  235.872612.163
   257.1 2611.03  265.662612.163   279.8 2613.56     311 2613.28   367.1 2617.18
   378.8 2616.07   512.5 2615.03   559.7 2620.05   586.3 2626.99   600.9  2632.8
#Mann= 4 ,-1,0
       0      .1       0     100     .06       0  235.87    .045       0
  265.66      .1       0
#XS Ineff= 2 , 0
                        361.9419            2620
Permanent Ineff=
       F       F
Bank Sta=235.87,265.66
XS Rating Curve= 0 ,0
Exp/Cntr=0.3,0.1