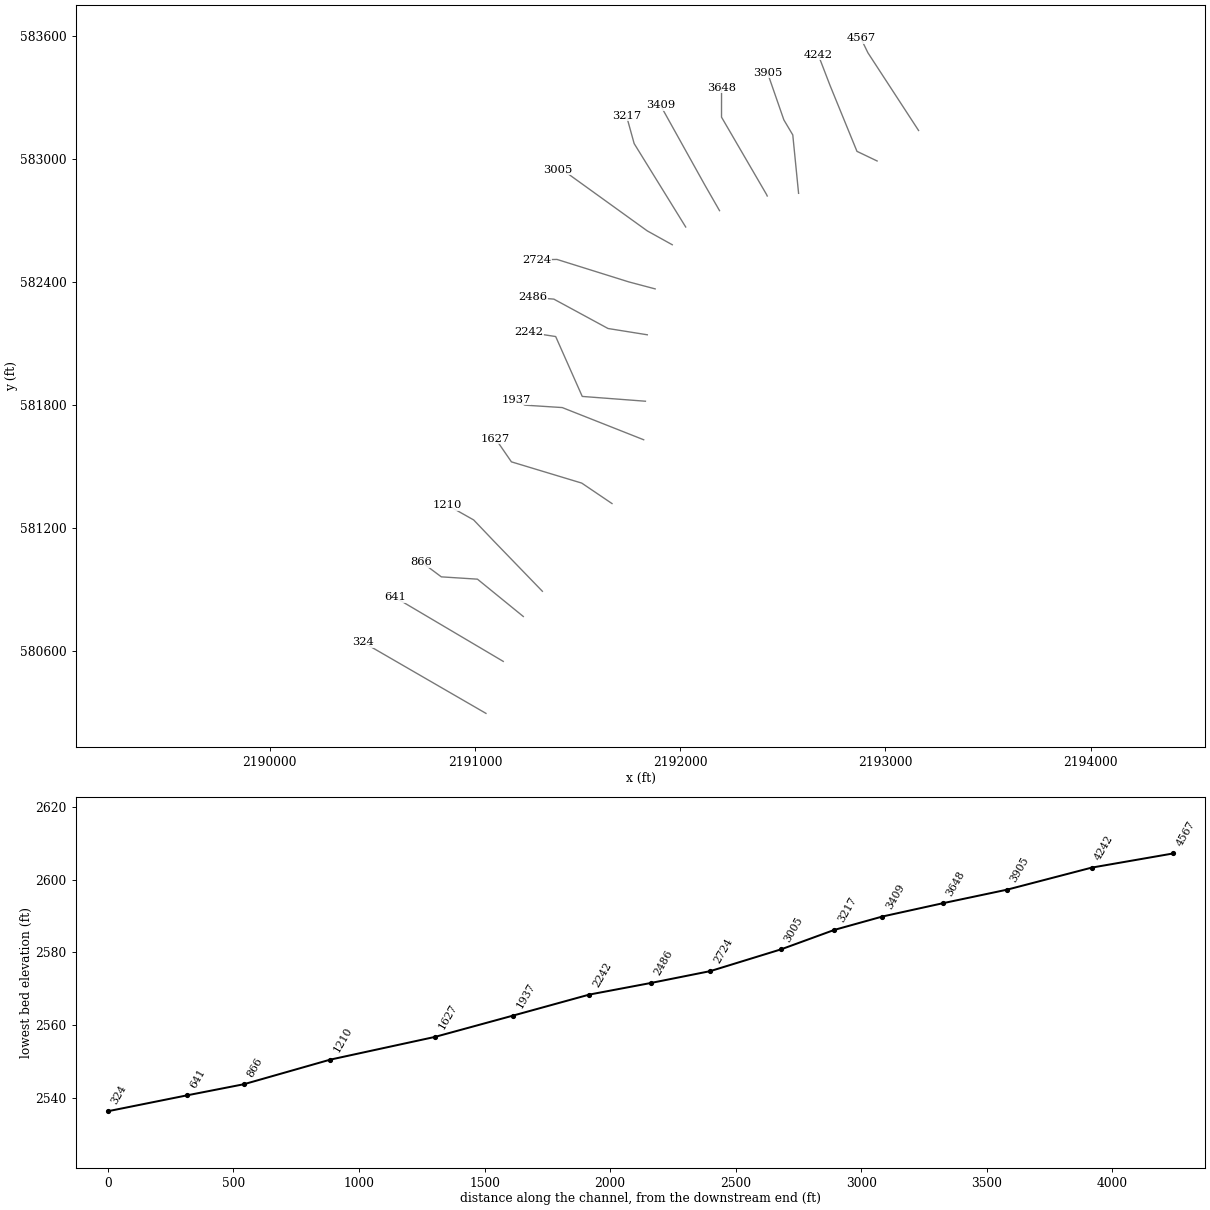
HEC-RAS study SUGARCK.prj: SUGARCK

--- SUGARCK.g01 (geometry) --- (continued)

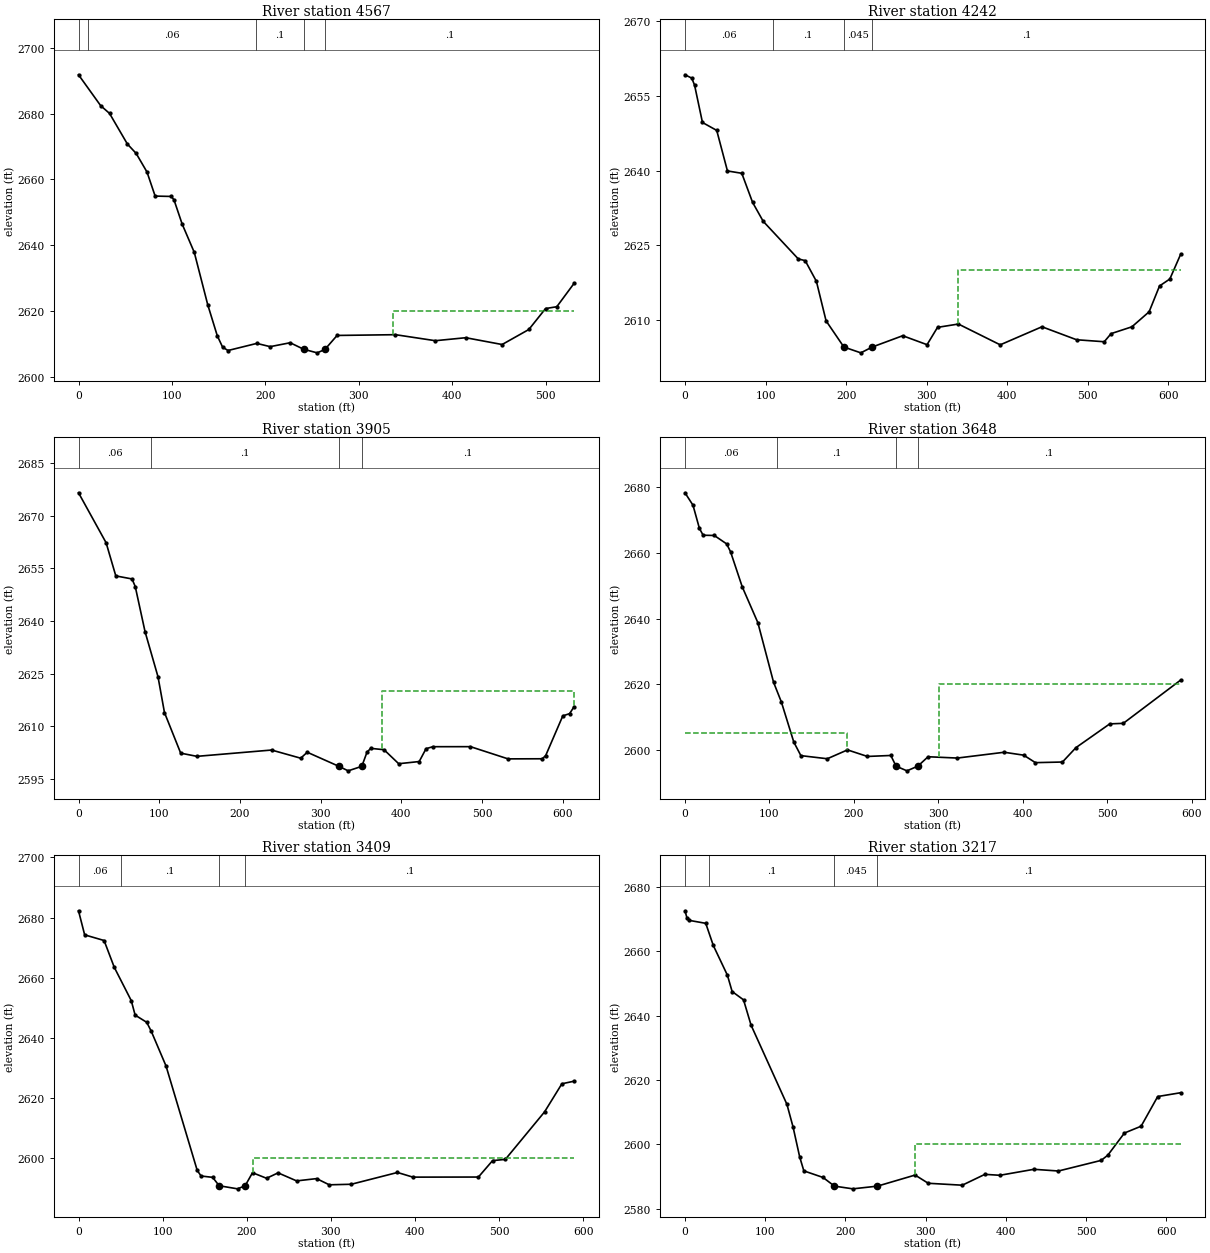
Type RM Length L Ch R = 1 ,4567    ,325.4,325.4,325.4
XS GIS Cut Line= 3
2193161.81302473583137.3669170742192914.96703067 583515.96541448
2192880.61969688583586.490985502
#Sta/Elev= 30
       0 2691.82    23.7 2682.43    33.2 2680.07    52.3 2670.76    61.7  2667.9
    73.3 2662.24      82 2654.93    99.3 2654.82   102.2 2653.77   110.9 2646.43
   123.9  2637.8   138.3 2621.87   148.5 2612.45   154.2 2608.98     160 2607.97
   190.8 2610.13   205.1 2609.14   226.5 2610.33     241 2608.34   255.4 2607.26
  263.63 2608.28   276.7 2612.55   339.2 2612.78   381.8 2610.95   414.4 2611.86
   453.3 2609.79   481.9 2614.36   499.8 2620.73   511.8 2621.28   530.4 2628.43
#Mann= 5 ,-1,0
       0      .1       0      10     .06       0     190      .1       0
     241    .045       0  263.63      .1       0
#XS Ineff= 2 , 0
                        337.0208            2620
Permanent Ineff=
       F       F
Bank Sta=241,263.63
XS Rating Curve= 0 ,0
Exp/Cntr=0.3,0.1

Type RM Length L Ch R = 1 ,4242    ,336.8,336.8,336.8
XS GIS Cut Line= 4
2192959.72379307582988.8408116612192861.54596443583035.824853237
2192730.03788599583357.6548278322192673.06824713583505.711425259
#Sta/Elev= 30
       0 2659.24     8.4 2658.57    11.9 2657.16    21.7 2649.65    39.4 2648.06
    52.7 2639.91    70.5 2639.44    83.9 2633.59    97.1 2629.78   140.6 2622.23
   149.2 2621.88   163.1 2617.72   175.1 2609.78  197.232604.513   218.2 2603.35
  232.322604.514   270.2 2606.79   300.4 2604.99   313.4 2608.47   339.3 2609.14
   391.2 2604.96     443 2608.59     486 2605.98   520.3 2605.58   528.8 2607.21
   554.6 2608.58     576  2611.6   588.9 2616.79   601.7 2618.19   615.1 2623.15
#Mann= 4 ,-1,0
       0     .06       0  108.84      .1       0  197.23    .045       0
  232.32      .1       0
#XS Ineff= 2 , 0
                        339.4264            2620
Permanent Ineff=
       F       F
Bank Sta=197.23,232.32
XS Rating Curve= 0 ,0
Exp/Cntr=0.3,0.1

Type RM Length L Ch R = 1 ,3905    ,256.8,256.8,256.8
XS GIS Cut Line= 4
2192577.04971472582831.1955692352192548.79337683583115.785621217
2192505.40794977583188.8719224492192425.60081935583418.562311296
#Sta/Elev= 30
       0 2676.53    34.2 2662.28    46.2 2652.84    66.3 2651.97    70.3  2649.8
    82.4 2636.98    98.5 2624.08   106.5 2613.89   126.6 2602.32   146.7 2601.41
   239.2 2603.21   275.3 2600.88   283.4 2602.58  322.592598.568   334.1 2597.28
     3512598.568   357.4 2602.58     362 2603.69   378.5  2603.3   396.7 2599.31
   422.1 2599.93   430.6  2603.6   439.1 2604.16   485.6 2604.17   532.2 2600.69
   574.6 2600.72   578.8 2601.63     600 2612.94   608.4 2613.58   614.1 2615.58
#Mann= 4 ,-1,0
       0     .06       0      90      .1       0  322.59    .045       0
     351      .1       0
#XS Ineff= 2 , 0
                         375.415            2620
Permanent Ineff=
       F       F
Bank Sta=322.59,351
XS Rating Curve= 0 ,0
Exp/Cntr=0.3,0.1

Type RM Length L Ch R = 1 ,3648    ,239.9,239.9,239.9
XS GIS Cut Line= 5
 2192424.2641317582818.2195882042192420.59535694582826.075027238
2192289.57975418 583051.141966312192201.53874913583202.428720859
2192201.68398007583345.117223612
#Sta/Elev= 30
       0 2678.37     9.5 2674.57    17.1 2667.49    21.5 2665.42    34.7 2665.34
    49.3 2662.78    53.9 2660.41    67.8 2649.67    86.3 2638.73   104.9 2620.54
   114.1 2614.55   128.8 2602.33   137.2 2598.17   168.5 2597.22   192.4 2599.92
     216 2597.92   243.7 2598.22  249.852594.967   262.8 2593.53   275.72594.968
   287.8 2597.83   322.4 2597.43   377.9  2599.2     401 2598.31   414.9 2596.03
   446.9 2596.22   462.9 2600.62   502.9 2607.86   518.9 2608.02   586.8 2621.22
#Mann= 4 ,-1,0
       0     .06       0  108.67      .1       0  249.85    .045       0
   275.7      .1       0
#XS Ineff= 2 , 0
          192.38    2605 300.234            2620
Permanent Ineff=
       F       F
Bank Sta=249.85,275.7
XS Rating Curve= 0 ,0
Exp/Cntr=0.3,0.1

Type RM Length L Ch R = 1 ,3409    ,191.2,191.2,191.2
XS GIS Cut Line= 3
 2192191.8252634582746.8042024512192121.20155791582869.914841945
 2191903.7619533583260.643214687
#Sta/Elev= 30
       0 2682.28     7.3 2674.28    30.4  2672.4    42.5 2663.49    62.7 2652.42
    67.3 2647.61    81.1 2645.21    86.5 2642.22     104 2630.72   141.1 2595.99
   145.7 2594.14   159.4  2593.7  167.18 2590.91     189 2589.88  198.072590.908
   206.8 2595.24   223.5 2593.39   237.2 2595.19   259.2 2592.52     283 2593.28
     298 2591.22   324.2  2591.4   379.1 2595.32   397.4 2593.77   475.3  2593.8
   492.1 2599.25   507.3 2599.67   553.9 2615.45   574.5 2624.79   589.1 2625.66
#Mann= 4 ,-1,0
       0     .06       0      50      .1       0  167.18    .045       0
  198.07      .1       0
#XS Ineff= 2 , 0
                           206.8            2600
Permanent Ineff=
       F       F
Bank Sta=167.18,198.07
XS Rating Curve= 0 ,0
Exp/Cntr=0.3,0.1

Type RM Length L Ch R = 1 ,3217    ,212,212,212
XS GIS Cut Line= 3
2192026.96745102582667.1160890512191775.83890789583073.588205322
2191738.38452859583208.669573268
#Sta/Elev= 30
       0 2672.59     2.4 2670.45     5.3 2669.61    25.9 2668.69    35.3 2661.82
    52.9 2652.57    58.8  2647.5      73 2644.92    82.4 2637.05   127.1 2612.46
   134.7 2605.47     143 2596.13   148.2 2591.78   172.1 2589.74  186.342587.042
   209.3  2586.2     2402587.043   286.9 2590.48   303.3 2587.93   345.7 2587.33
   373.9  2590.7   392.7 2590.41     435 2592.27   465.6 2591.74   518.9 2595.04
   527.2 2596.66   547.9 2603.54   568.7 2605.66   589.4 2614.88617.9697 2616.06
#Mann= 4 ,-1,0
       0     .06       0      30      .1       0  186.34    .045       0
     240      .1       0
#XS Ineff= 2 , 0
                          286.89            2600
Permanent Ineff=
       F       F
Bank Sta=186.34,240
XS Rating Curve= 0 ,0
Exp/Cntr(USF)=0,0
Exp/Cntr=0.3,0.1

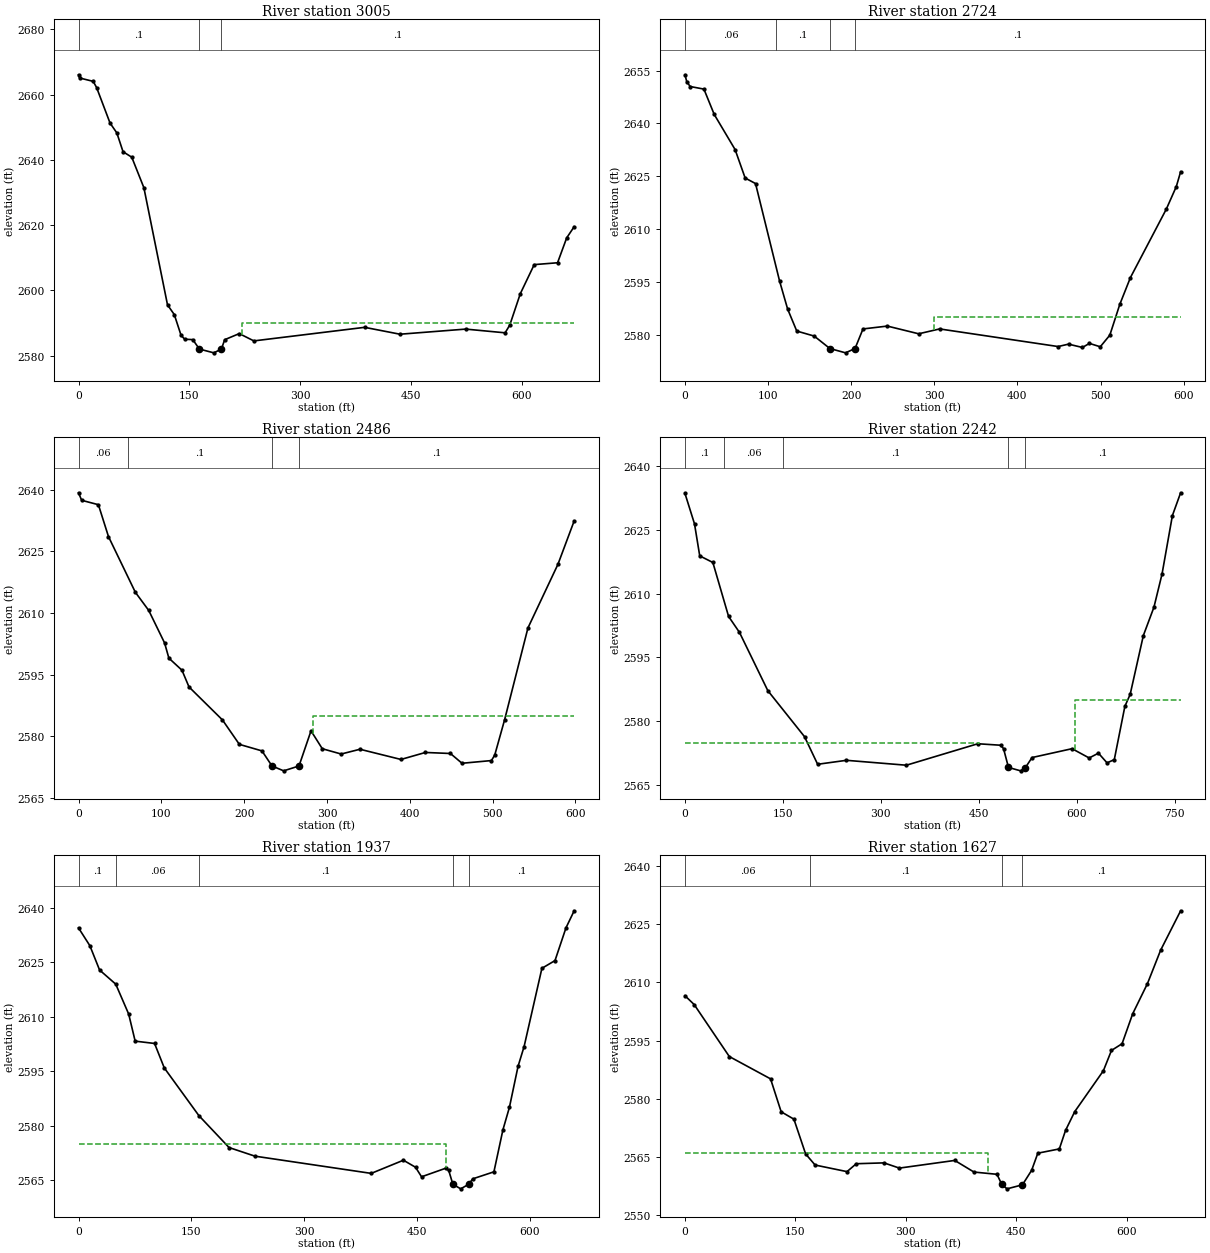
Type RM Length L Ch R = 1 ,3005    ,281.9,281.9,281.9
XS GIS Cut Line= 4
2191961.56466444582580.5750433642191839.46884114582648.365099338
2191438.46527115582937.267438204 2191402.3780268582946.362594692
#Sta/Elev= 30
       0 2666.11     1.6 2665.12    19.9 2664.09    24.5 2662.19    42.7  2651.3
    51.9 2648.28    60.3 2642.51    72.1 2640.84    88.5 2631.49   120.5 2595.56
   129.7 2592.57   138.8 2586.26   143.7 2585.03   154.7  2584.9  163.692582.005
   183.2 2580.85  193.492582.003   197.9 2584.88   217.7 2586.75   237.4 2584.51
   387.4 2588.67   435.3 2586.56   524.2 2588.13   577.6 2586.99   583.9 2589.35
   598.2    2599     617  2607.9   648.6 2608.47     661 2616.11   671.1 2619.53
#Mann= 3 ,-1,0
       0      .1       0  163.69    .045       0  193.49      .1       0
#XS Ineff= 2 , 0
                        220.9684            2590
Permanent Ineff=
       F       F
Bank Sta=163.69,193.49
XS Rating Curve= 0 ,0
Exp/Cntr=0.3,0.1

Type RM Length L Ch R = 1 ,2724    ,237.6,237.6,237.6
XS GIS Cut Line= 4
 2191878.1966916582365.5219083812191750.10613833582399.476767131
2191399.69164993 582509.120286232191303.02282309582507.120094363
#Sta/Elev= 30
       0 2653.83     2.1 2651.91     6.2  2650.5    22.8 2649.76    35.2 2642.56
    60.3 2632.59    72.4 2624.51    84.9 2622.93   113.8 2595.27   123.5  2587.3
   134.5 2581.04   155.5 2579.61  174.332576.076   193.2 2574.85  204.632576.075
   214.2 2581.64   243.5 2582.45   281.2 2580.26   306.4 2581.64   448.9 2576.64
   461.5 2577.32   478.2 2576.38   486.7 2577.53   499.7 2576.57   511.2 2579.87
   523.2 2588.62     536 2596.24   579.2 2615.69   591.2 2622.08   596.4 2626.29
#Mann= 4 ,-1,0
       0     .06       0     110      .1       0  174.33    .045       0
  204.63      .1       0
#XS Ineff= 2 , 0
                        299.8367            2585
Permanent Ineff=
       F       F
Bank Sta=174.33,204.63
XS Rating Curve= 0 ,0
Exp/Cntr=0.3,0.1

Type RM Length L Ch R = 1 ,2486    ,244,244,244
XS GIS Cut Line= 4
2191839.88690091582141.8625343352191648.51903968582172.494396412
2191384.50992638582315.6772555262191280.61081425 582324.36524965
#Sta/Elev= 30
       0 2639.22     3.8 2637.39      24 2636.32    36.2 2628.55    68.6 2615.02
    84.8 2610.59   103.9 2602.69   109.1 2598.99   124.9 2596.05   133.4 2591.98
   173.8 2583.95   194.2 2578.01   221.5 2576.42  233.572572.755   247.7 2571.57
   266.22572.755   280.7  2581.3   294.3 2576.95   317.1 2575.66   339.8 2576.82
   389.3 2574.34   418.8 2576.04     449 2575.79     463 2573.41   498.5 2574.07
   502.5  2575.4   514.4 2583.98   542.6 2606.34   578.8 2621.81   598.4 2632.37
#Mann= 4 ,-1,0
       0     .06       0      60      .1       0  233.57    .045       0
   266.2      .1       0
#XS Ineff= 2 , 0
                        283.2046            2585
Permanent Ineff=
       F       F
Bank Sta=233.57,266.2
XS Rating Curve= 0 ,0
Exp/Cntr=0.3,0.1

Type RM Length L Ch R = 1 ,2242    ,304.5,304.5,304.5
XS GIS Cut Line= 4
2191830.75616956581818.1620622242191522.87334519581841.477684877
2191393.39001897582133.3157548012191263.79400936582153.287855432
#Sta/Elev= 30
       0  2633.5    14.6 2626.36    22.6 2618.85    42.7  2617.3    66.8 2604.63
    83.5 2600.88   126.9 2587.21   183.1 2576.41   203.2 2569.93   247.3 2570.86
   339.1 2569.71   448.5 2574.75   483.5  2574.4   487.9 2573.62   495.5 2569.19
   514.1 2568.39  521.45 2569.15   531.6 2571.51   592.9 2573.59   619.1 2571.41
   633.3 2572.54   646.5 2570.26   657.6 2571.03   673.8 2583.53   681.9 2586.34
   702.1 2600.15   718.3 2606.79   730.7 2614.57   746.6 2628.32   759.2 2633.66
#Mann= 5 ,-1,0
       0      .1       0      60     .06       0     150      .1       0
   495.5    .045       0  521.45      .1       0
#XS Ineff= 2 , 0
        449.7087    2575597.5739            2585
Permanent Ineff=
       F       F
Bank Sta=495.5,521.45
XS Rating Curve= 0 ,0
Exp/Cntr=0.3,0.1

Type RM Length L Ch R = 1 ,1937    ,310.4,310.4,310.4
XS GIS Cut Line= 4
2191822.23847397581630.3713525742191425.37598635581787.222006834
2191243.12825816581798.9766677642191201.06511248581825.100231724
#Sta/Elev= 30
       0 2634.53    15.1 2629.62      28 2622.92    49.5 2619.02    66.7 2610.77
    75.3 2603.31   101.1 2602.67     114 2595.93     160 2582.78   200.1 2573.98
   234.5  2571.6   389.1 2566.85   431.9 2570.48     448 2568.54     456 2565.91
   488.1 2568.27   492.1 2567.67  497.642563.846   508.1 2562.59  518.592563.844
   524.1 2565.35   552.2 2567.28   564.2 2578.88   572.8 2585.05   584.3 2596.38
   592.3  2601.8     616 2623.39   633.4 2625.52     648 2634.55658.8756 2639.25
#Mann= 5 ,-1,0
       0      .1       0      50     .06       0     160      .1       0
  497.64    .045       0  518.59      .1       0
#XS Ineff= 2 , 0
           488.1    2575
Permanent Ineff=
       F       F
Bank Sta=497.64,518.59
XS Rating Curve= 0 ,0
Exp/Cntr=0.3,0.1

Type RM Length L Ch R = 1 ,1627    ,417,417,417
XS GIS Cut Line= 4
2191667.85210927581319.4649446512191520.44143886581419.148870323
2191177.73554721581522.6929930462191099.99374338581635.553658362
#Sta/Elev= 30
       0 2606.56    12.5 2604.28    60.2 2590.87   116.2 2585.11   130.6 2576.61
   147.9 2574.71   163.8 2565.74   176.7 2562.87     220 2561.17   232.6 2563.21
   270.2 2563.43   291.1 2562.08   366.3 2564.06   392.4 2561.06   423.7 2560.48
   430.1 2557.87   437.3 2556.73   458.2 2557.77   470.7 2561.51   479.1 2565.93
   508.3 2567.03   516.7 2571.79   529.2 2576.65   568.1  2587.2   579.1 2592.44
   593.5 2594.18   607.9  2601.9     628 2609.71   645.8 2618.29673.0032 2628.48
#Mann= 4 ,-1,0
       0     .06       0     170      .1       0   430.1    .045       0
   458.2      .1       0
#XS Ineff= 2 , 0
           410.8    2566
Permanent Ineff=
       F       F
Bank Sta=430.1,458.2
XS Rating Curve= 0 ,0
Exp/Cntr=0.3,0.1

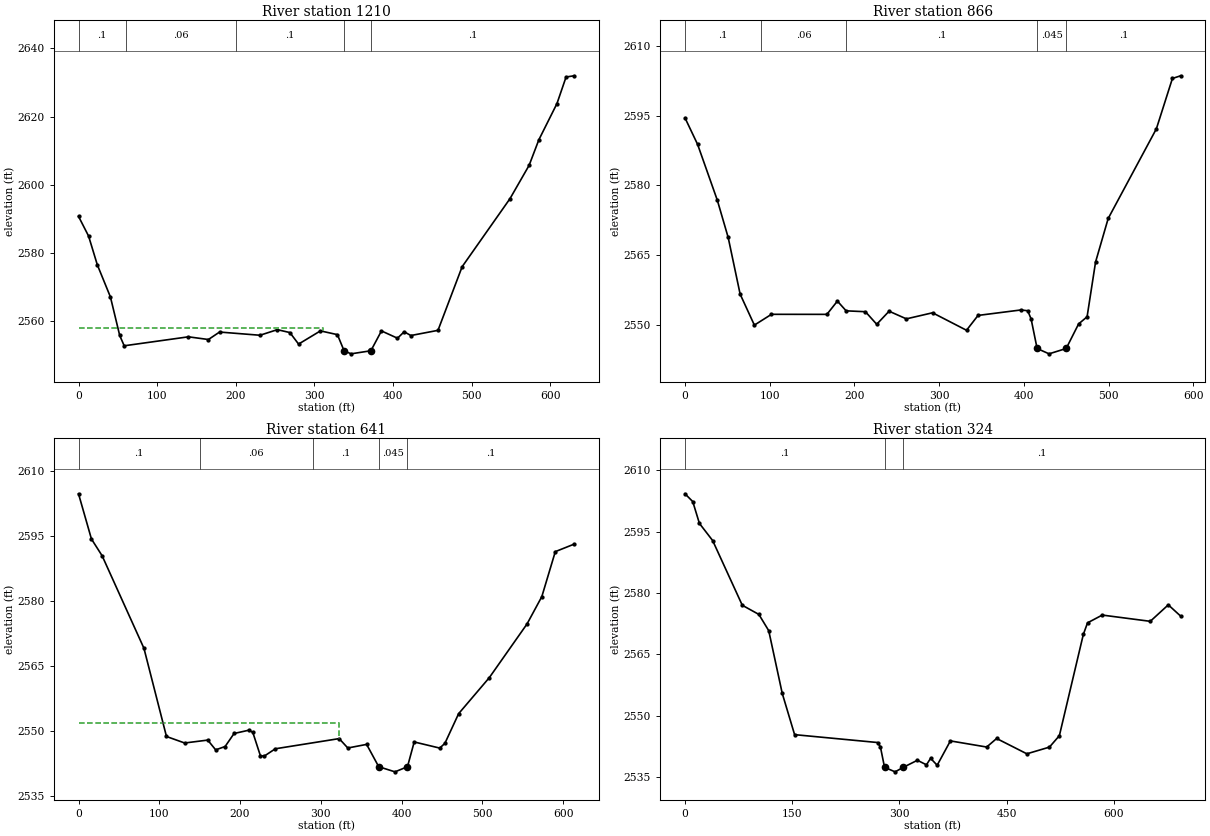
Type RM Length L Ch R = 1 ,1210    ,343.8,343.8,343.8
XS GIS Cut Line= 4
2191328.59233269580891.9758473062191094.88977724581133.621987404
2190993.81254014 581239.57275671 2190865.0808736581312.171400854
#Sta/Elev= 30
       0 2590.78    12.8 2585.01    23.9 2576.58    40.6 2567.14    52.4 2555.85
    58.1 2552.83   139.8 2555.46   165.2 2554.67   179.4 2556.86   230.8 2555.92
   252.9 2557.56   268.8 2556.71   279.9 2553.33   307.7  2557.2   329.3  2556.1
  337.752551.375   346.6 2550.47  371.872551.374   385.3 2557.19   405.7 2555.05
   414.2 2556.94   422.7 2555.84   457.2 2557.36   487.9 2576.01   548.8 2595.98
   573.1 2605.74   585.5 2613.24   608.5 2623.84   620.1 2631.64   630.4    2632
#Mann= 5 ,-1,0
       0      .1       0      60     .06       0     200      .1       0
  337.75    .045       0  371.87      .1       0
#XS Ineff= 2 , 0
        310.9396    2558
Permanent Ineff=
       F       F
Bank Sta=337.75,371.87
XS Rating Curve= 0 ,0
Exp/Cntr=0.3,0.1

Type RM Length L Ch R = 1 ,866     ,225.6,225.6,225.6
XS GIS Cut Line= 4
 2191235.7005444580769.0618145362191012.15501891580951.042882531
2190836.13357054580962.2688239312190739.69053015581034.300724276
#Sta/Elev= 30
       0 2594.57    14.9 2588.85    38.2  2576.8      51 2568.78    65.1 2556.57
    81.9 2549.89   102.1 2552.22   167.5 2552.21   179.9 2555.07   190.2 2552.97
     213 2552.78   226.3 2550.07   240.9 2552.89   261.3 2551.24   292.2 2552.55
   332.3 2548.78   345.9 2551.98   396.5 2553.16   404.5 2552.99   408.5 2551.24
  415.612544.854   429.7  2543.7  449.932544.852   464.6 2550.15   474.6 2551.69
   484.6 2563.49   499.5 2572.88   556.4 2592.22   575.3 2603.06585.0057 2603.64
#Mann= 5 ,-1,0
       0      .1       0      90     .06       0     190      .1       0
  415.61    .045       0  449.93      .1       0
Bank Sta=415.61,449.93
XS Rating Curve= 0 ,0
Exp/Cntr=0.3,0.1

Type RM Length L Ch R = 1 ,641     ,316.1,316.1,316.1
XS GIS Cut Line= 2
2191137.93521583580550.3158781432190609.72491325580862.655802568
#Sta/Elev= 30
       0 2604.67      16 2594.26    29.2 2590.41      81  2569.1   108.9 2548.79
   131.4 2547.29     160 2547.96   169.8 2545.71   181.5 2546.48   192.6 2549.48
   211.2 2550.25   215.8 2549.73   225.1  2544.4   229.7 2544.24   243.7 2545.96
   322.7  2548.3   333.4 2546.14   356.7 2546.97  371.692541.827   391.8 2540.65
  407.282541.828   415.6 2547.53   447.2 2546.12   453.6 2547.21   470.6 2554.04
   508.6 2562.34   555.3  2574.7   573.6 2580.99   590.3 2591.35613.6468 2593.08
#Mann= 5 ,-1,0
       0      .1       0     150     .06       0     290      .1       0
  371.69    .045       0  407.28      .1       0
#XS Ineff= 2 , 0
           322.7    2552
Permanent Ineff=
       F       F
Bank Sta=371.69,407.28
XS Rating Curve= 0 ,0
Exp/Cntr(USF)=0,0
Exp/Cntr=0.3,0.1

Type RM Length L Ch R = 1 ,324     ,,,
XS GIS Cut Line= 2
2191053.64922686580297.0152327312190453.25753573580644.268805437
#Sta/Elev= 30
       0  2604.3    10.9 2602.39    20.2 2597.05    38.7 2592.86    80.2 2577.02
   103.4 2574.78   117.2  2570.8   136.1 2555.46   153.4 2545.36   269.7 2543.43
   273.5 2542.35  279.25 2537.37     294 2536.26   305.7 2537.38   325.2 2539.09
   337.9 2537.98   343.7 2539.57   352.9 2537.87   371.4 2543.83   422.2 2542.33
   436.1 2544.42   478.4 2540.67     510 2542.31   523.9 2545.11   557.4 2569.87
   563.3 2572.72   583.9 2574.62   651.1 2573.09   676.3 2577.12693.5814 2574.37
#Mann= 3 ,-1,0
       0      .1       0  279.25    .045       0   305.7      .1       0
Bank Sta=279.25,305.7
XS Rating Curve= 0 ,0
Exp/Cntr(USF)=0,0
Exp/Cntr=0.3,0.1
LCMann Table=0

Chan Stop Cuts=-1
Use User Specified Reach Order=0
Composite Channel Slope=5